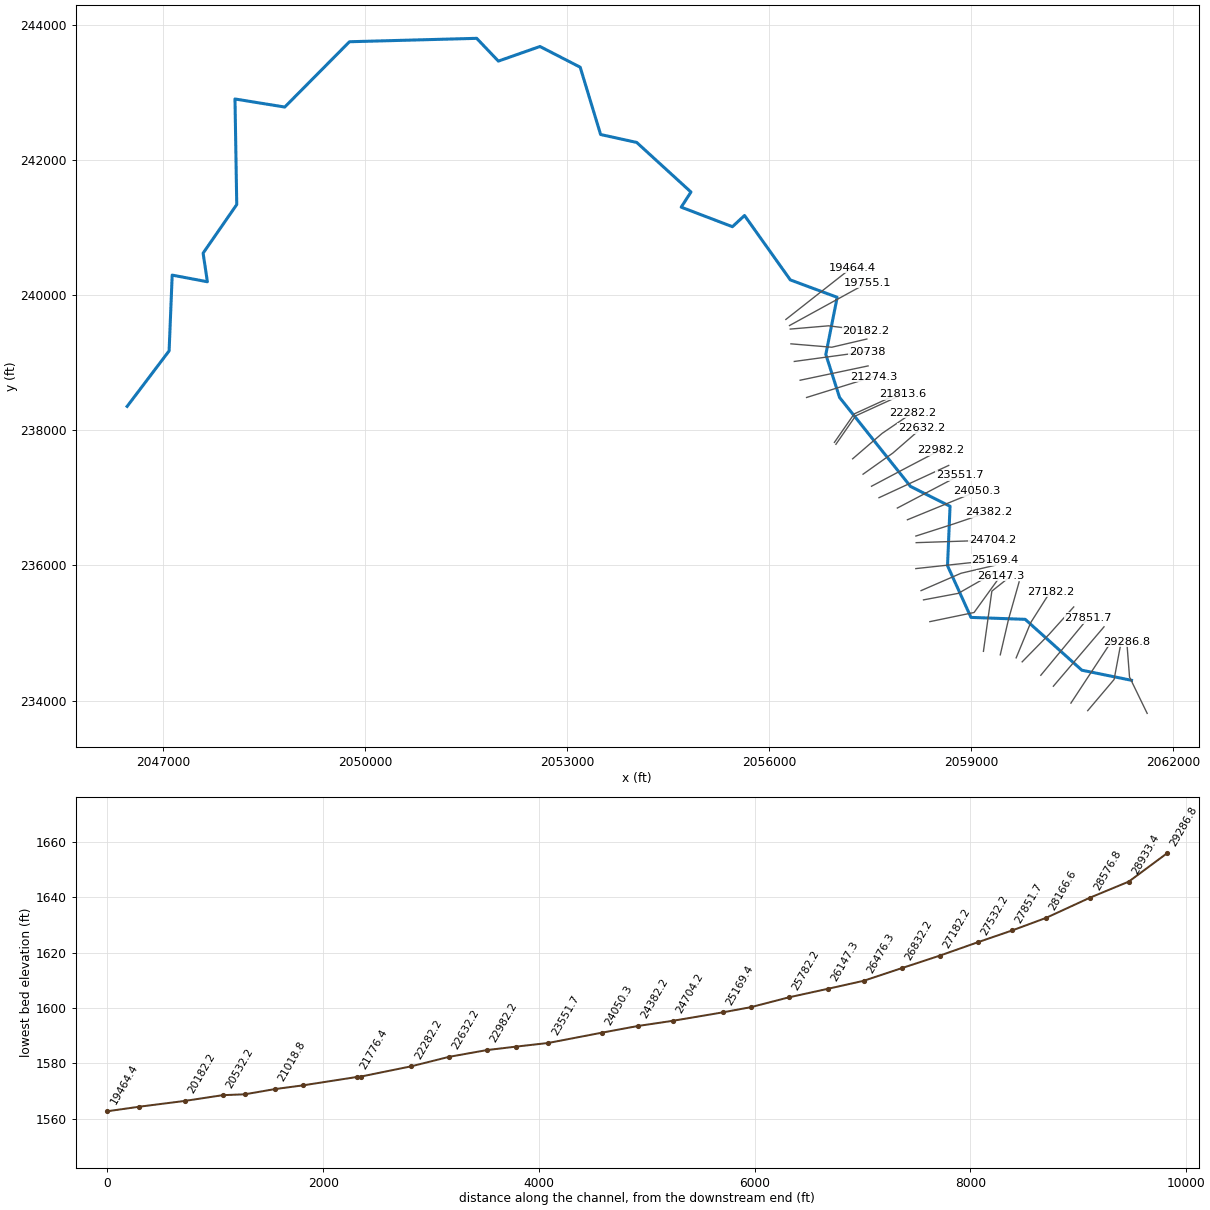
--- KELLYCK.prj (project) ---

Proj Title=KELLYCK
Current Plan=p01
Default Exp/Contr=0,0
English Units
Geom File=g01
Flow File=f01
Plan File=p01
BEGIN DESCRIPTION:
END DESCRIPTION:
DSS Export Rating Curves= 0
DSS Export Rating Curve Sorted= 0
DSS Export Volume Flow Curves= 0
DXF OffsetX= 0
DXF OffsetY= 0
DXF ScaleX= 0
DXF ScaleY= 0

--- KELLYCK.p01 (plan) ---

Plan Title=Floodplain
Program Version=4.00
Geom File=g01
Flow File=f01
K Sum by GR=0
Std Step Tol=0.01
Critical Tol=0.01
Num of Std Step Trials=20
Max Error Tol=0.3
Flow Tol Ratio=0.001
Split Flow NTrial=30
Split Flow Tol=0.02
Split Flow Ratio=0.02
Log Output Level=0
Friction Slope Method=1
Unsteady Friction Slope Method=2
Unsteady Bridges Friction Slope Method=1
Global Log Level=0
CheckData=False
Run HTab=0
Run UNet=0
Run PostProcess=0
UNET Theta=0
UNET Theta Warmup=0
UNET ZTol=0
UNET ZSATol=0
UNET MxIter=0
UNET MaxInSteps=0
UNET DtIC=0
UNET DtMin=0
UNET MaxCRTS=0
UNET WFStab=0
UNET SFStab=0
UNET WFX=0
UNET SFX=0
UNET DSS MLevel=0
UNET DZMax Abort=0
UNET Convert EG Bridges=0
UNET Use Existing IB Tables=0
UNET Froude Limit=0
UNET Froude Power=0
Write IC File=0
Echo Input=False
Echo Output=False
Write Detailed=0

--- KELLYCK.f01 (steady flow) ---

Flow Title=2010 USGS WV Regression Equation
Program Version=4.00
Number of Profiles=1
Profile Names=P100yr
River Rch & RM=KELLYCK,Main      ,29286.8
438.6421
River Rch & RM=KELLYCK,Main      ,28933.4
439.8786
River Rch & RM=KELLYCK,Main      ,28576.8
666.0652
River Rch & RM=KELLYCK,Main      ,27532.2
709.9342
River Rch & RM=KELLYCK,Main      ,25782.2
783.7784
River Rch & RM=KELLYCK,Main      ,23551.7
826.7516
River Rch & RM=KELLYCK,Main      ,23253.2
979.2985
River Rch & RM=KELLYCK,Main      ,19464.4
1046.905
River Rch & RM=KELLYCK,Main      ,19161
1182.488
River Rch & RM=KELLYCK,Main      ,12416.5
1269.964
River Rch & RM=KELLYCK,Main      ,7218.5
1408.645
River Rch & RM=KELLYCK,Main      ,6881.9
1410.088
Boundary for River Rch & Prof#=KELLYCK,Main      ,1
Up Type=0
Dn Type=3
Dn Slope=0.002633

--- KELLYCK.g01 (geometry) ---

Geom Title=LiDAR
Program Version=4.10

River Reach=KELLYCK         ,Main
Reach XY= 30
     2061379.052      234301.054     2060642.073       234450.36
     2059800.927      235202.964     2058996.239       235231.61
     2058648.149      235996.367     2058685.475      236875.707
      2058098.67       237169.11     2057045.718      238485.082
     2056841.725      239121.367     2057010.128      239966.853
     2056314.816      240223.798     2055635.021      241176.799
     2055455.333      241011.001     2054694.916      241300.063
     2054839.882      241524.022     2054034.326      242257.528
     2053498.736      242374.716     2053195.785      243370.376
     2052598.562      243676.799     2051981.375      243460.654
     2051659.326      243797.459     2049771.305      243747.112
     2048810.491      242781.054     2048071.891      242900.178
     2048097.932      241338.719     2047598.635      240620.009
     2047662.177      240196.572     2047139.781      240295.009
     2047093.948      239174.176     2046471.046      238353.108

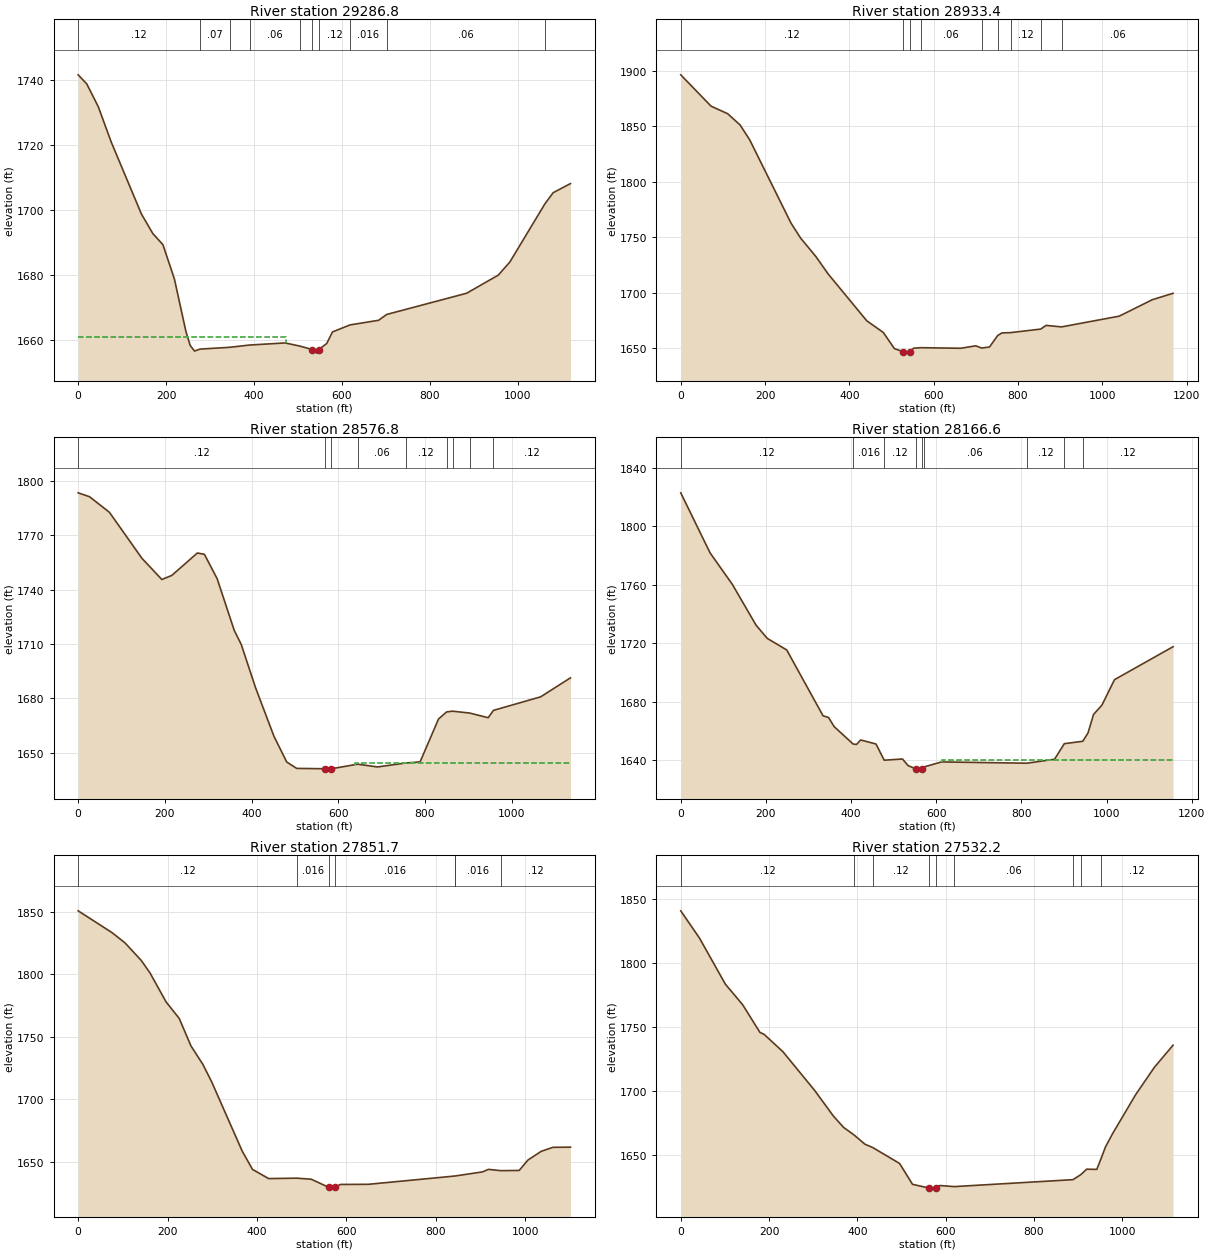
Type RM Length L Ch R = 1 ,29286.8 ,378.9,353.3,326.3
XS GIS Cut Line= 3
     2061611.492      233811.883     2061349.495      234349.344
     2061309.235      234869.248
#Sta/Elev= 30
       0 1741.53    19.6 1738.73    45.7 1731.74    75.2 1720.84   143.8  1698.7
   169.9 1692.64   192.8 1689.24   218.9 1678.66     245 1662.54   254.8 1658.21
   264.6  1656.5  277.14  1657.1   344.21657.651  389.741658.348   470.5    1659
  503.88 1658.03   532.6 1656.95   542.4 1655.86  547.341656.967   565.2 1658.83
   578.3 1662.39   618.31664.546   683.2 1665.97  701.491667.763   883.2 1674.29
   955.4 1679.88   981.6 1683.91 1060.921701.739    1080 1705.24  1119.4 1708.05
#Mann= 10 ,-1 , 0
       0     .12       0  277.14     .07       0   344.2     .12       0
  389.74     .06       0  503.88     .12       0   532.6    .045       0
  547.34     .12       0   618.3    .016       0  701.49     .06       0
 1060.92     .12       0
#XS Ineff= 2 , 0
          472.54 1660.71
Permanent Ineff=
       F       F
Bank Sta=532.6,547.34
XS Rating Curve= 0 ,0
Exp/Cntr=0.3,0.1

Type RM Length L Ch R = 1 ,28933.4 ,353.7,356.6,358.9
XS GIS Cut Line= 3
     2060728.822      233851.921     2061120.328      234312.886
      2061224.54      234866.167
#Sta/Elev= 30
       0 1896.25    71.9 1868.03   111.2 1861.26   140.6 1851.18   163.5 1837.75
   261.5 1762.76   284.4 1749.21   320.4  1732.7   349.8 1716.88   441.3 1674.76
   480.6 1664.23   506.7 1649.78   526.3 1647.07   536.1 1645.67   542.7 1647.02
   552.5 1650.11  569.431650.567   663.7 1650.05   699.7 1652.24  713.751650.257
   732.4 1651.19  751.69 1661.48   761.9 1663.85  782.681664.141     8541667.333
   866.6 1670.65  903.37 1669.28  1040.1 1678.96  1118.7 1693.78  1167.8 1699.55
#Mann= 9 ,-1 , 0
       0     .12       0   526.3    .045       0   542.7     .12       0
  569.43     .06       0  713.75     .12       0  751.69     .06       0
  782.68     .12       0     854    .016       0  903.37     .06       0
Bank Sta=526.3,542.7
XS Rating Curve= 0 ,0
Exp/Cntr=0.3,0.1

Type RM Length L Ch R = 1 ,28576.8 ,410.3,410.2,406.9
XS GIS Cut Line= 2
     2060479.703      233963.927     2061104.703      234911.844
#Sta/Elev= 30
       0 1793.43    26.2 1791.29      72 1782.72   147.2 1757.28     193 1745.62
     216 1747.87   274.9 1760.24   291.2 1759.51   320.7 1745.98   359.9 1717.61
   376.3  1709.7     409 1686.02   451.6 1659.13     481 1644.97   503.9 1641.43
   569.3 1641.23   575.9 1639.92  584.121641.228   644.71643.752   690.4 1642.23
  756.311644.422   788.6 1645.01   831.1 1668.67  849.751672.579  863.351672.993
   902.91671.955   945.6 1669.39  957.871673.433  1066.7  1680.9  1135.4 1691.38
#Mann= 9 ,-1 , 0
       0     .12       0   569.3    .045       0  584.12     .12       0
   644.7     .06       0  756.31     .12       0  849.75     .06       0
  863.35     .08       0   902.9    .016       0  957.87     .12       0
#XS Ineff= 2 , 0
                          638.58         1644.63
Permanent Ineff=
       F       F
Bank Sta=569.3,584.12
XS Rating Curve= 0 ,0
Exp/Cntr=0.3,0.1

Type RM Length L Ch R = 1 ,28166.6 ,311.6,314.9,314.1
XS GIS Cut Line= 2
     2060219.287      234213.927     2060971.023        235092.4
#Sta/Elev= 30
       0 1822.98    68.8 1781.92   121.2 1760.34   176.9 1732.41   203.1  1723.4
   248.9 1715.47   334.1 1670.47   347.2 1669.23   360.3 1663.01  404.661651.146
   412.7 1650.81   422.5 1653.89   458.6 1651.13   477.81640.052   520.8 1640.86
   533.9 1636.37  552.161634.033   563.4 1632.57  567.671634.017  570.271635.345
   612.5 1638.87  812.931637.983   877.8 1640.69  900.771651.351  944.211653.001
   956.4 1658.69   969.5 1671.36   989.2 1677.75  1018.6 1695.14  1156.2  1717.7
#Mann= 9 ,-1 , 0
       0     .12       0  404.66    .016       0   477.8     .12       0
  552.16    .045       0  567.67     .12       0  570.27     .06       0
  812.93     .12       0  900.77    .016       0  944.21     .12       0
#XS Ineff= 2 , 0
                          613.29         1640.23
Permanent Ineff=
       F       F
Bank Sta=552.16,567.67
XS Rating Curve= 0 ,0
Exp/Cntr=0.3,0.1

Type RM Length L Ch R = 1 ,27851.7 ,320.7,319.5,317.7
XS GIS Cut Line= 2
     2060032.829      234375.733     2060735.954      235222.955
#Sta/Elev= 30
       0 1850.58    75.4 1833.24   104.9 1824.91   140.9 1810.99   160.6 1800.98
   196.6 1777.77   226.1 1764.49   252.3 1742.53   278.5 1728.05   298.2 1714.14
     367 1658.34   389.9  1643.8     426 1636.45   488.81636.781     521 1635.96
   560.3 1629.49   570.2 1628.02  574.971629.495   586.5 1631.77   648.8 1631.86
  842.451638.499  842.591638.507   904.4 1641.81   917.5 1643.82     9451642.798
   986.3 1642.96    1006 1651.31  1035.4 1658.21  1061.7 1661.45    1101 1661.58
#Mann= 7 ,-1 , 0
       0     .12       0   488.8    .016       0   560.3    .045       0
  574.97    .016       0  842.45     .08       0  842.59    .016       0
     945     .12       0
Bank Sta=560.3,574.97
XS Rating Curve= 0 ,0
Exp/Cntr=0.3,0.1

Type RM Length L Ch R = 1 ,27532.2 ,338.5,350,347
XS GIS Cut Line= 3
     2059756.125      234574.402     2060156.333      234981.579
     2060521.152      235386.183
#Sta/Elev= 30
       0 1840.77    42.4 1819.55   101.1 1783.59   140.3 1767.55   179.4    1746
   189.2 1744.35   231.6 1730.89   303.4 1700.76   345.8  1680.8   368.7 1671.98
  393.091665.886   417.6 1658.74  434.721656.239   495.9 1643.78   525.2 1627.51
  562.331624.608   570.9 1623.75   577.4 1624.55   587.2 1626.56  619.821625.712
  888.881631.136  906.461635.023     920 1639.31   942.8 1639.14  953.431648.383
   962.4 1656.57   978.7 1667.04  1030.9 1697.42  1073.3 1718.73  1115.7 1736.01
#Mann= 9 ,-1 , 0
       0     .12       0  393.09    .016       0  434.72     .12       0
  562.33    .045       0   577.4     .12       0  619.82     .06       0
  888.88     .12       0  906.46    .016       0  953.43     .12       0
Bank Sta=562.33,577.4
XS Rating Curve= 0 ,0
Exp/Cntr=0.3,0.1

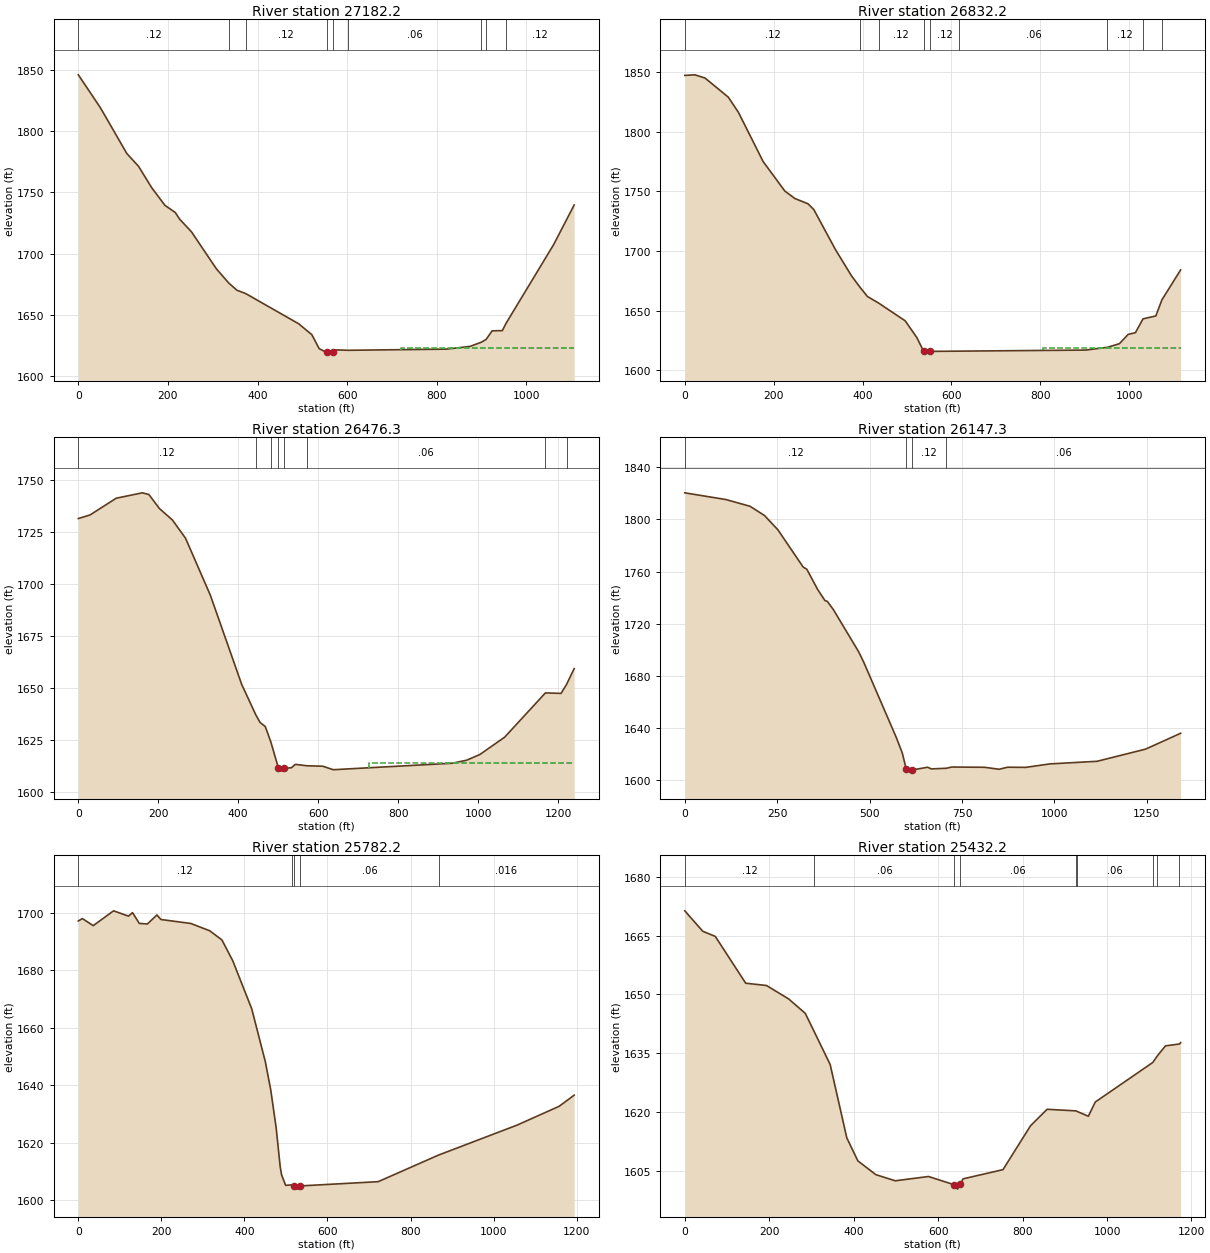
Type RM Length L Ch R = 1 ,27182.2 ,345.3,350,355.6
XS GIS Cut Line= 3
     2059666.813      234633.169     2059882.766       235154.12
     2060174.199       235612.09
#Sta/Elev= 30
       0 1845.84    49.2 1819.07   108.2 1781.72   134.4 1771.27   163.9 1753.74
   193.4  1739.4   216.4 1733.61   226.2 1728.14   252.5 1717.88   308.2 1687.66
  335.941676.037   354.1 1670.21  373.851667.447   491.8  1642.9   521.3 1633.96
   537.7 1622.53   554.1 1619.59   560.7 1618.94  568.62 1619.71     577 1621.59
  602.551621.251   822.3  1622.2   874.6 1624.45  899.861627.878  910.391630.156
   923.6  1637.1   946.5  1637.3  954.621643.154    1061 1707.41  1106.8 1739.72
#Mann= 9 ,-1 , 0
       0     .12       0  335.94    .016       0  373.85     .12       0
   554.1    .045       0  568.62     .12       0  602.55     .06       0
  899.86     .12       0  910.39    .016       0  954.62     .12       0
#XS Ineff= 2 , 0
                          720.22         1623.19
Permanent Ineff=
       F       F
Bank Sta=554.1,568.62
XS Rating Curve= 0 ,0
Exp/Cntr=0.3,0.1

Type RM Length L Ch R = 1 ,26832.2 ,350.1,355.9,358.7
XS GIS Cut Line= 3
     2059430.951      234677.871     2059553.917      235205.246
     2059710.975      235757.378
#Sta/Elev= 30
       0 1847.06    22.8 1847.55    45.7 1844.82    97.9 1828.84   120.7 1816.13
   176.2 1774.95   225.1 1750.22   247.9 1743.92   277.3 1739.53   290.3 1734.69
   339.3 1700.98   375.2 1679.14   395.21669.163     411 1661.89  436.75 1656.24
   495.8 1641.55     522 1627.56  537.341616.049   544.8 1614.46   551.4 1615.92
  617.731616.127   902.3 1617.02  951.02 1619.34   977.8 1622.34   997.5 1630.11
  1013.9  1631.6 1031.021643.175  1059.8 1645.59 1073.441659.053  1115.6 1684.15
#Mann= 9 ,-1 , 0
       0     .12       0   395.2    .016       0  436.75     .12       0
  537.34    .045       0   551.4     .12       0  617.73     .06       0
  951.02     .12       0 1031.02    .016       0 1073.44     .12       0
#XS Ineff= 2 , 0
                          805.01         1618.63
Permanent Ineff=
       F       F
Bank Sta=537.34,551.4
XS Rating Curve= 0 ,0
Exp/Cntr=0.3,0.1

Type RM Length L Ch R = 1 ,26476.3 ,356,329,298.8
XS GIS Cut Line= 3
     2059181.093      234729.552     2059306.093      235620.177
     2059573.454      235831.983
#Sta/Elev= 30
       0  1731.3    29.4 1733.04    94.8 1741.08   160.2 1743.67   176.6 1742.86
   202.8 1736.13   235.5 1730.58   268.2 1721.85   330.3 1694.43   408.8  1651.5
  443.971636.934   454.6 1633.27   467.7 1631.28  481.611623.883   500.4 1611.43
   506.9 1609.85   515.4 1611.18   533.1 1611.49   542.9  1613.1  572.36 1612.42
   611.6 1612.21   637.7 1610.53   935.4 1613.64   971.5  1615.1  1004.3 1617.82
  1066.6 1626.19 1168.561647.474  1207.6 1647.22 1221.281651.494  1240.4 1659.13
#Mann= 8 ,-1 , 0
       0     .12       0  443.97    .016       0  481.61     .12       0
   500.4    .045       0   515.4     .12       0  572.36     .06       0
 1168.56    .016       0 1221.28     .12       0
#XS Ineff= 2 , 0
                          727.74          1613.8
Permanent Ineff=
       F       F
Bank Sta=500.4,515.4
XS Rating Curve= 0 ,0
Exp/Cntr=0.3,0.1

Type RM Length L Ch R = 1 ,26147.3 ,364.5,365.1,371.8
XS GIS Cut Line= 3
     2058385.954      235168.789     2059042.204      235304.205
     2059436.301      235847.608
#Sta/Elev= 30
       0 1820.42   111.1 1815.27   176.5 1810.11   215.7    1803   251.7 1792.12
   320.3 1763.48   330.1 1761.82   359.6  1746.2   379.2 1737.79   385.7 1737.14
     402 1730.83   470.7 1698.34   483.8 1690.71     572 1632.88   588.4 1620.84
   599.3 1608.23     608 1606.98   614.3 1607.85     657 1609.96   666.8 1608.69
  706.961609.168   722.5 1610.12   810.9 1609.93   850.2 1608.41   873.1 1609.97
   922.2 1609.86   987.7 1612.52  1115.4 1614.52  1246.4 1623.84  1341.3 1636.01
#Mann= 4 ,-1 , 0
       0     .12       0   599.3    .045       0   614.3     .12       0
  706.96     .06       0
Bank Sta=599.3,614.3
XS Rating Curve= 0 ,0
Exp/Cntr=0.3,0.1

Type RM Length L Ch R = 1 ,25782.2 ,345.1,350,330.3
XS GIS Cut Line= 3
     2058291.653       235490.79     2058807.964      235587.334
     2059389.301      235917.984
#Sta/Elev= 30
       0 1697.12     9.8 1697.94    35.9 1695.49    84.8 1700.64   120.7  1698.8
   130.5 1700.01   146.8 1696.27   166.4 1696.07   189.2  1699.2     199 1697.62
   270.8 1696.25   316.5  1693.7   345.8 1690.52   371.9 1683.28   417.6 1666.56
   450.2 1648.24   463.3 1638.43   476.3 1625.32   486.1 1611.68   489.4 1608.88
   499.2 1605.18  515.351605.373  519.841604.924   528.5 1603.87  534.041604.983
     722 1606.46  867.591615.718  1056.4 1626.12    1158 1632.68    1194 1636.54
#Mann= 5 ,-1 , 0
       0     .12       0  515.35     .06       0  519.84    .045       0
  534.04     .06       0  867.59    .016       0
Bank Sta=519.84,534.04
XS Rating Curve= 0 ,0
Exp/Cntr=0.3,0.1

Type RM Length L Ch R = 1 ,25432.2 ,268.8,262.8,241.3
XS GIS Cut Line= 3
     2058255.405      235627.726     2058848.223      235884.429
     2059362.613      236004.646
#Sta/Elev= 30
       0 1671.34    42.6 1666.12    72.1 1664.83   144.3 1652.87   193.5 1652.29
   245.9 1648.87   285.3 1645.19  306.571640.506   344.3 1632.13   383.7 1613.42
   409.9 1607.55   452.5 1604.03   498.4 1602.47   577.2 1603.56   638.5 1601.45
     646 1600.34   652.5 1601.56     659 1602.96   753.6 1605.31   818.8  1616.5
     858 1620.71  926.561620.302   929.91620.128   955.8 1618.94   972.1 1622.56
 1108.341632.651  1119.21634.342  1138.4 1636.89  1171.41637.366  1174.3  1637.7
#Mann= 9 ,-1 , 0
       0     .12       0  306.57     .06       0   638.5    .045       0
   652.5     .06       0  926.56     .08       0   929.9     .06       0
 1108.34     .08       0  1119.2    .016       0  1171.4     .06       0
Bank Sta=638.5,652.5
XS Rating Curve= 0 ,0
Exp/Cntr=0.3,0.1

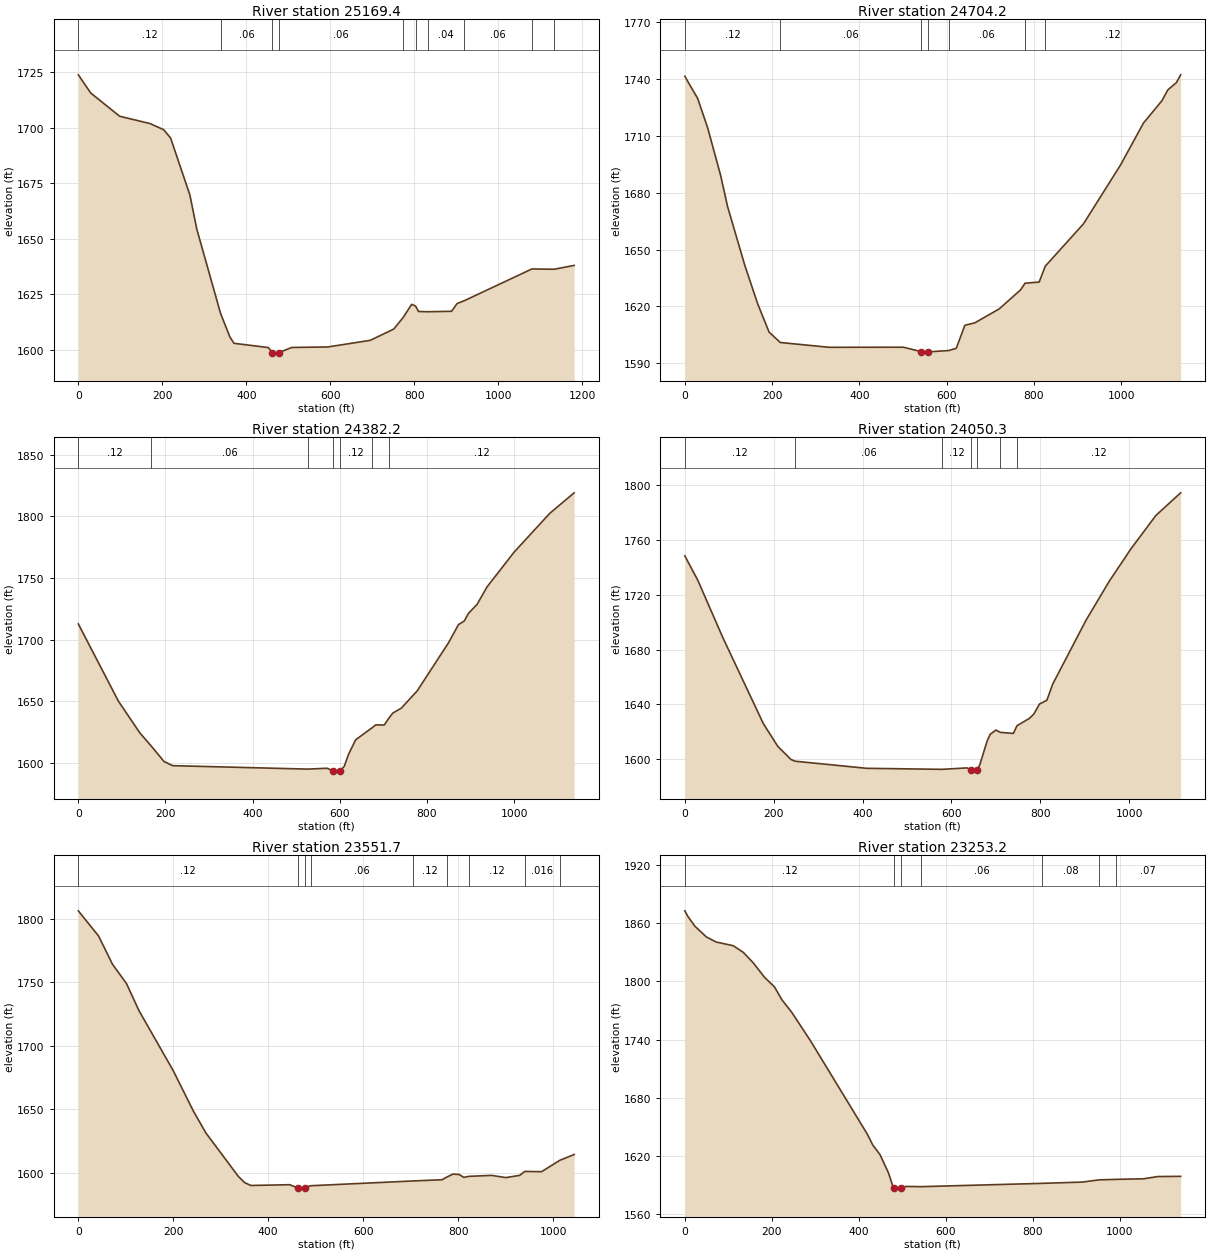
Type RM Length L Ch R = 1 ,25169.4 ,461.1,465.2,472.9
XS GIS Cut Line= 2
      2058177.62       235953.51     2059351.231      236080.247
#Sta/Elev= 30
       0 1723.89    29.5  1715.7    98.4 1705.22   170.5 1701.93   203.3 1699.15
   219.7  1695.4   265.6 1669.72     282 1654.35   338.71616.302   360.7 1605.78
   370.5 1602.87   452.5 1600.94  461.841598.707   465.6 1598.44  477.211598.658
   508.2    1601   593.5 1601.21   695.1 1604.21   750.9 1609.28  773.291614.497
   793.5 1620.42  802.851619.652   809.9 1617.21  832.561617.101   888.6 1617.29
   901.7 1620.79  919.211622.107 1079.891636.383 1132.831636.251  1180.4 1637.98
#Mann= 10 ,-1 , 0
       0     .12       0   338.7     .06       0  461.84    .045       0
  477.21     .06       0  773.29     .12       0  802.85     .08       0
  832.56     .04       0  919.21     .06       0 1079.89    .016       0
 1132.83     .12       0
Bank Sta=461.84,477.21
XS Rating Curve= 0 ,0
Exp/Cntr=0.3,0.1

Type RM Length L Ch R = 1 ,24704.2 ,306.5,322,328.5
XS GIS Cut Line= 2
     2058182.828      236337.191     2059318.586      236374.582
#Sta/Elev= 30
       0 1741.45    29.5 1729.78    52.4 1714.27    81.9 1689.38    98.2  1672.6
   137.5 1641.74     167 1621.45   193.2 1606.46  218.841600.994   330.8 1598.45
     501  1598.5   542.2 1596.15   546.9 1595.38   557.2 1596.05   605.11596.741
   622.2 1597.94   641.9 1610.07   664.8 1611.37   720.5  1618.7   769.6 1628.76
  779.841632.268   812.2 1632.88  826.161641.264   913.7 1663.58   998.8 1694.71
  1051.2 1716.76  1093.8 1728.64  1106.9 1734.24  1126.6  1738.1  1136.4 1742.23
#Mann= 7 ,-1 , 0
       0     .12       0  218.84     .06       0   542.2    .045       0
   557.2     .12       0   605.1     .06       0  779.84    .016       0
  826.16     .12       0
Bank Sta=542.2,557.2
XS Rating Curve= 0 ,0
Exp/Cntr=0.3,0.1

Type RM Length L Ch R = 1 ,24382.2 ,330.2,331.9,332.5
XS GIS Cut Line= 3
     2058178.373       236435.08     2058740.894      236614.767
     2059259.247      236790.058
#Sta/Elev= 30
       0 1712.79    91.9 1650.24   141.1 1624.54  167.38 1613.81   196.8 1601.26
   216.5 1597.94  526.331595.161   570.8 1595.85     584 1593.84   597.1 1593.52
   600.4 1593.71   610.2  1597.4     620 1607.12   636.4 1618.92  673.82 1628.58
   682.3 1631.01   701.9 1630.87  712.081636.172   721.6 1640.56   741.2  1644.6
   777.3 1658.43   849.4  1697.5   872.3 1712.26   885.4  1715.1   895.2 1721.31
   914.9 1728.61   937.8 1742.79  1000.1 1771.01    1082 1802.47  1137.7    1819
#Mann= 7 ,-1 , 0
       0     .12       0  167.38     .06       0  526.33     .12       0
     584    .045       0   600.4     .12       0  673.82    .016       0
  712.08     .12       0
Bank Sta=584,600.4
XS Rating Curve= 0 ,0
Exp/Cntr=0.3,0.1

Type RM Length L Ch R = 1 ,24050.3 ,492,498.5,497.2
XS GIS Cut Line= 2
      2058052.62      236675.733     2059085.606      237097.608
#Sta/Elev= 30
       0 1748.48    29.4 1730.53    85.1 1689.07   176.7 1625.88   209.4 1609.17
   238.9 1599.65     2481598.379     409 1593.18  579.411592.424   634.8 1593.49
   644.6 1592.03   651.2 1591.12  658.681592.185   664.2 1596.13   680.6 1613.33
   687.2 1618.02   700.2 1621.12   710.1 1619.45   739.5 1618.68  747.581624.316
   775.5 1629.67   785.3 1632.79   798.4 1640.21   814.8 1642.89   827.9  1654.7
   903.1 1701.51   955.5 1730.06  1004.6 1753.86  1060.2 1777.99  1115.8 1794.51
#Mann= 7 ,-1 , 0
       0     .12       0     248     .06       0  579.41     .12       0
   644.6    .045       0  658.68     .12       0   710.1    .016       0
  747.58     .12       0
Bank Sta=644.6,658.68
XS Rating Curve= 0 ,0
Exp/Cntr=0.3,0.1

Type RM Length L Ch R = 1 ,23551.7 ,297.8,298.5,297.3
XS GIS Cut Line= 2
     2057903.315      236849.344     2058828.662      237333.719
#Sta/Elev= 30
       0 1806.04    42.6 1786.28      72 1764.06   101.5  1748.9   127.7 1727.66
   199.7 1680.62   242.3 1648.76   268.5 1631.64   337.2 1597.35   350.3 1592.54
   363.4 1590.26   445.3 1590.86   461.7 1588.45   468.2 1587.39     478 1588.65
  489.561590.049  704.721593.802   766.2 1594.77   777.1 1597.02   789.1 1599.18
   802.2 1598.88     812 1596.64  823.241597.454   870.9 1598.19   900.4 1596.44
   929.9 1598.22  940.531601.303   975.7 1601.09  1014.61610.084  1044.5 1614.61
#Mann= 9 ,-1 , 0
       0     .12       0   461.7    .045       0     478     .12       0
  489.56     .06       0  704.72     .12       0   777.1    .016       0
  823.24     .12       0  940.53    .016       0  1014.6     .12       0
Bank Sta=461.7,478
XS Rating Curve= 0 ,0
Exp/Cntr=0.3,0.1

Type RM Length L Ch R = 1 ,23253.2 ,269.4,271,271.3
XS GIS Cut Line= 2
     2057630.745      237002.122     2058665.468      237479.552
#Sta/Elev= 30
       0 1872.51     6.6 1867.09    22.9 1856.81    49.1  1845.8      72 1840.41
   111.3 1836.61   134.3 1829.81   157.2 1819.04   183.4 1804.06   206.3 1794.13
   222.7 1781.26   245.6 1768.19   288.2 1739.24   419.2  1642.9   432.2 1631.39
   448.6 1621.63   468.3 1602.62   478.1 1589.21  480.721587.303   487.9 1586.07
   497.7 1587.22   507.6 1588.86  543.071588.605  820.64    1592   913.6 1593.33
  952.64  1595.6  990.231596.114  1054.4 1596.71  1087.2 1599.03  1139.6 1599.22
#Mann= 7 ,-1 , 0
       0     .12       0  480.72    .045       0   497.7     .12       0
  543.07     .06       0  820.64     .08       0  952.64    .016       0
  990.23     .07       0
Bank Sta=480.72,497.7
XS Rating Curve= 0 ,0
Exp/Cntr=0.3,0.1

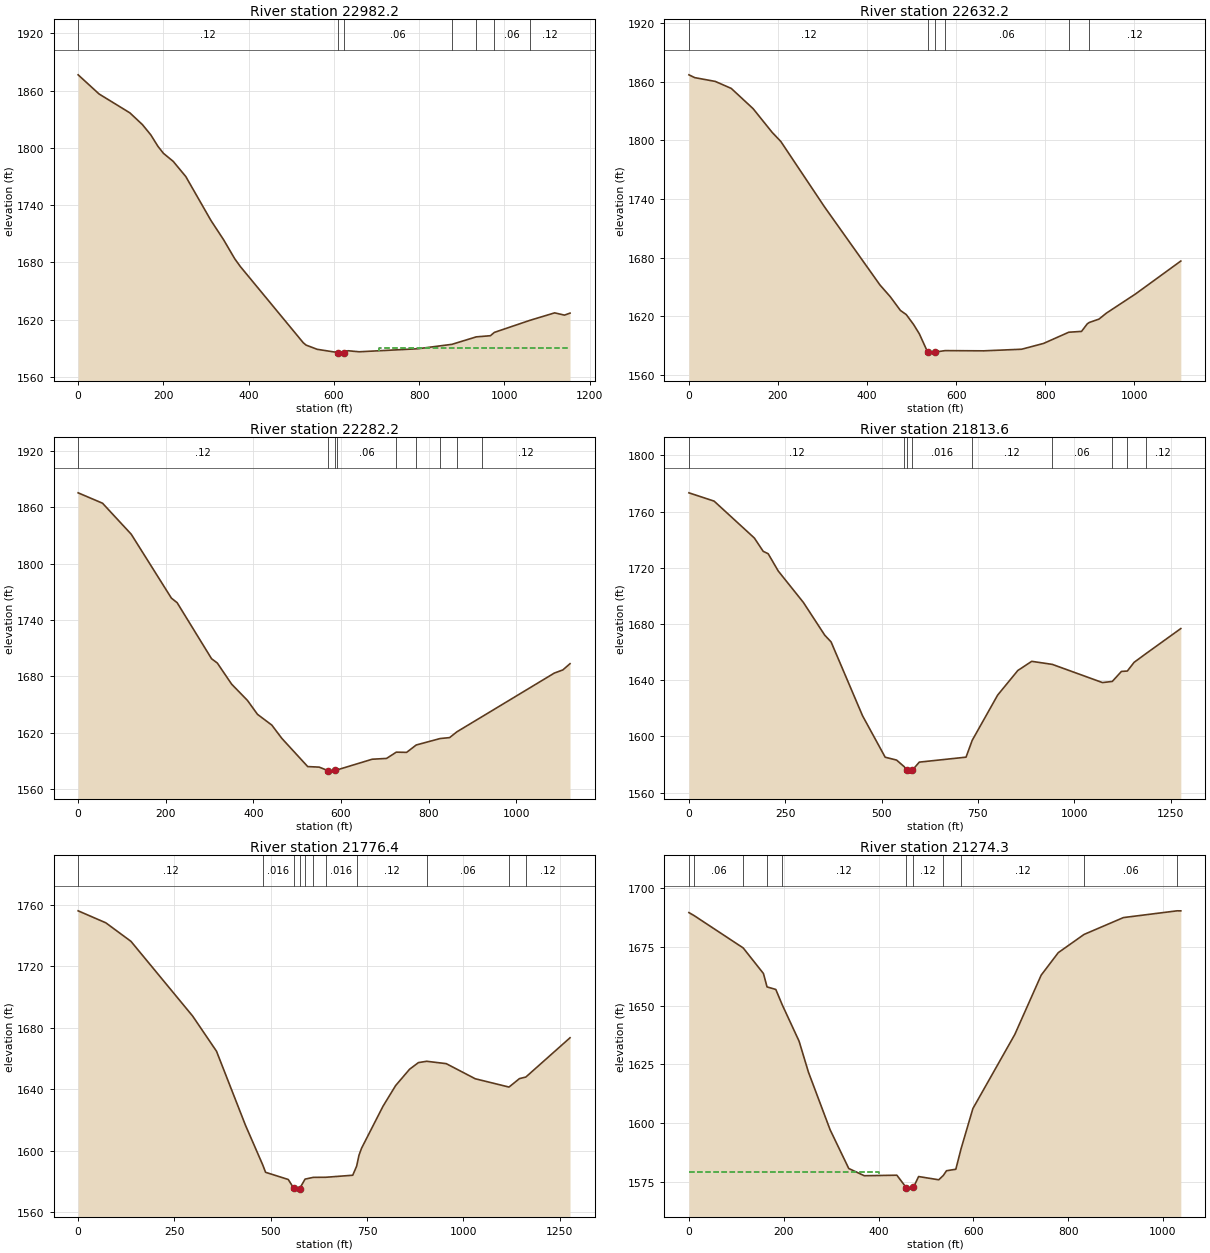
Type RM Length L Ch R = 1 ,22982.2 ,345.5,350,354.5
XS GIS Cut Line= 3
     2057520.032      237171.865     2058065.451      237459.693
      2058542.09      237707.949
#Sta/Elev= 30
       0 1876.53    49.2 1856.44   121.4 1836.66   150.9 1824.32   170.6 1813.52
     187 1801.76   200.1 1794.26   223.1 1785.82   252.6  1769.9   311.6 1723.88
   341.2 1703.74   367.4 1683.78   380.5 1675.62   528.1 1595.76   534.7 1593.26
   560.9 1588.82   609.2 1585.44   616.7 1584.82   624.2 1585.21   633.1 1587.32
   659.3 1586.23   796.9 1589.39   877.11594.041  934.121601.857   967.3 1603.07
  976.611606.559 1060.041619.195  1118.1 1627.03    1141 1624.65  1154.1 1626.76
#Mann= 7 ,-1 , 0
       0     .12       0   609.2    .045       0   624.2     .06       0
   877.1     .08       0  934.12    .016       0  976.61     .06       0
 1060.04     .12       0
#XS Ineff= 2 , 0
                          705.47         1590.27
Permanent Ineff=
       F       F
Bank Sta=609.2,624.2
XS Rating Curve= 0 ,0
Exp/Cntr=0.3,0.1

Type RM Length L Ch R = 1 ,22632.2 ,344.7,350,346.8
XS GIS Cut Line= 3
     2057394.451      237349.996     2057838.321      237664.052
     2058261.963      238031.555
#Sta/Elev= 30
       0 1866.91    13.1 1864.03      59 1860.19      95 1853.03   144.1 1832.33
   186.7 1808.19   206.4 1798.73   304.6 1731.82   429.1 1651.99     452 1640.12
     475 1625.98     488 1621.82   504.4 1611.73   517.5 1602.05   533.9 1585.58
   537.2 1583.53     547 1582.38  552.321583.468   575.41584.947   661.8 1584.72
   747.1 1586.36   796.3 1592.28  853.061603.762   881.6 1604.58   894.7 1612.42
   899.31613.775   920.9 1617.18   937.3 1623.22  1002.9 1642.87  1104.6 1676.54
#Mann= 6 ,-1 , 0
       0     .12       0   537.2    .045       0  552.32     .12       0
   575.4     .06       0  853.06    .016       0   899.3     .12       0
Bank Sta=537.2,552.32
XS Rating Curve= 0 ,0
Exp/Cntr=0.3,0.1

Type RM Length L Ch R = 1 ,22282.2 ,474.4,468.6,463
XS GIS Cut Line= 3
     2057239.812      237577.583     2057676.795      237953.245
     2058128.777      238259.972
#Sta/Elev= 30
       0 1875.43    55.7 1864.35   121.2 1831.32   212.8 1763.29   225.9 1758.42
   304.5 1698.69   317.6 1694.13   350.3 1671.61   386.4 1654.29   409.3 1639.47
     442 1628.01   464.9 1613.83   523.9 1583.82   550.1 1583.24   569.7 1579.58
   576.3 1578.97   586.1 1579.73  591.031580.293   671.1 1591.65   703.8  1592.5
  726.081599.181   749.6 1598.95  771.581606.824  826.261613.704   847.7 1614.67
  864.591620.917  922.24 1637.11  1086.5 1683.37  1106.1 1686.78  1122.5 1693.42
#Mann= 9 ,-1 , 0
       0     .12       0   569.7    .045       0   586.1     .12       0
  591.03     .06       0  726.08    .016       0  771.58     .06       0
  826.26    .016       0  864.59     .06       0  922.24     .12       0
Bank Sta=569.7,586.1
XS Rating Curve= 0 ,0
Exp/Cntr=0.3,0.1

Type RM Length L Ch R = 1 ,21813.6 ,38.5,37.3,37.1
XS GIS Cut Line= 3
      2056991.34      237792.225     2057284.309      238212.798
     2057979.621      238529.204
#Sta/Elev= 30
       0 1773.41    65.3 1767.51   169.8 1741.23   192.6 1731.79   205.7 1730.03
   231.8 1717.74   297.1 1695.33   352.6    1672   368.9 1667.26   450.5  1614.7
   509.3 1585.15   538.8 1583.13  558.731578.402   565.1 1576.04   571.6 1575.25
   580.1 1576.03   597.8 1581.66   719.1 1585.19  735.231597.226   801.1 1629.37
   853.5  1646.9   889.6 1653.43  943.081651.251  1073.2  1638.3 1098.611639.107
  1122.4 1646.24 1137.671646.523  1155.2  1652.7 1185.541658.811  1276.5 1676.77
#Mann= 9 ,-1 , 0
       0     .12       0  558.73    .016       0   565.1    .045       0
   580.1    .016       0  735.23     .12       0  943.08     .06       0
 1098.61    .016       0 1137.67     .06       0 1185.54     .12       0
Bank Sta=565.1,580.1
XS Rating Curve= 0 ,0
Exp/Cntr=0.3,0.1

Type RM Length L Ch R = 1 ,21776.4 ,502.8,502.1,499.1
XS GIS Cut Line= 3
     2056969.205      237820.871     2057262.174      238241.444
     2057957.486       238557.85
#Sta/Elev= 30
       0 1756.13    71.8 1748.34   137.1 1736.28   297.1  1687.7   359.1  1664.8
   434.2 1616.68  479.291590.737   486.4 1586.05   545.3 1581.37  559.951575.521
     565  1575.1   574.8 1575.48  588.921581.606  610.311582.754  642.761582.813
   712.6 1584.13  722.681589.995   728.9 1597.19   735.5 1601.71   791.2 1629.02
     824 1642.49   860.1 1653.07     883 1657.39  904.511658.259   955.2 1656.73
  1030.6 1646.89 1118.15 1641.49  1145.3 1646.99 1161.781647.997  1276.5 1673.55
#Mann= 11 ,-1 , 0
       0     .12       0  479.29    .016       0  559.95    .045       0
   574.8    .016       0  588.92     .06       0  610.31     .08       0
  642.76    .016       0  722.68     .12       0  904.51     .06       0
 1118.15    .016       0 1161.78     .12       0
Bank Sta=559.95,574.8
XS Rating Curve= 0 ,0
Exp/Cntr=0.3,0.1

Type RM Length L Ch R = 1 ,21274.3 ,256,255.5,253
XS GIS Cut Line= 2
     2056556.093      238484.761     2057547.412      238792.052
#Sta/Elev= 30
       0 1689.49   11.231688.177  114.531674.474   157.2 1663.62   164.81657.933
   183.3 1656.85   196.71650.403   232.4 1634.89   252.1 1621.76   297.9 1597.26
   337.2 1580.82     370 1577.75   438.7 1577.97   458.4 1572.74   464.9 1572.06
  473.651572.834   484.6  1577.4   527.1 1576.03  536.651577.859   543.5 1579.87
   563.1  1580.5   573.91589.017   599.1 1606.27   687.5 1637.72   743.2 1662.93
   779.2 1672.47  833.641680.213   916.7 1687.37 1029.961690.238  1037.8 1690.23
#Mann= 11 ,-1 , 0
       0     .12       0   11.23     .06       0  114.53     .12       0
   164.8    .016       0   196.7     .12       0   458.4    .045       0
  473.65     .12       0  536.65    .016       0   573.9     .12       0
  833.64     .06       0 1029.96     .08       0
#XS Ineff= 2 , 0
           401.6 1579.29
Permanent Ineff=
       F       F
Bank Sta=458.4,473.65
XS Rating Curve= 0 ,0
Exp/Cntr=0.3,0.1

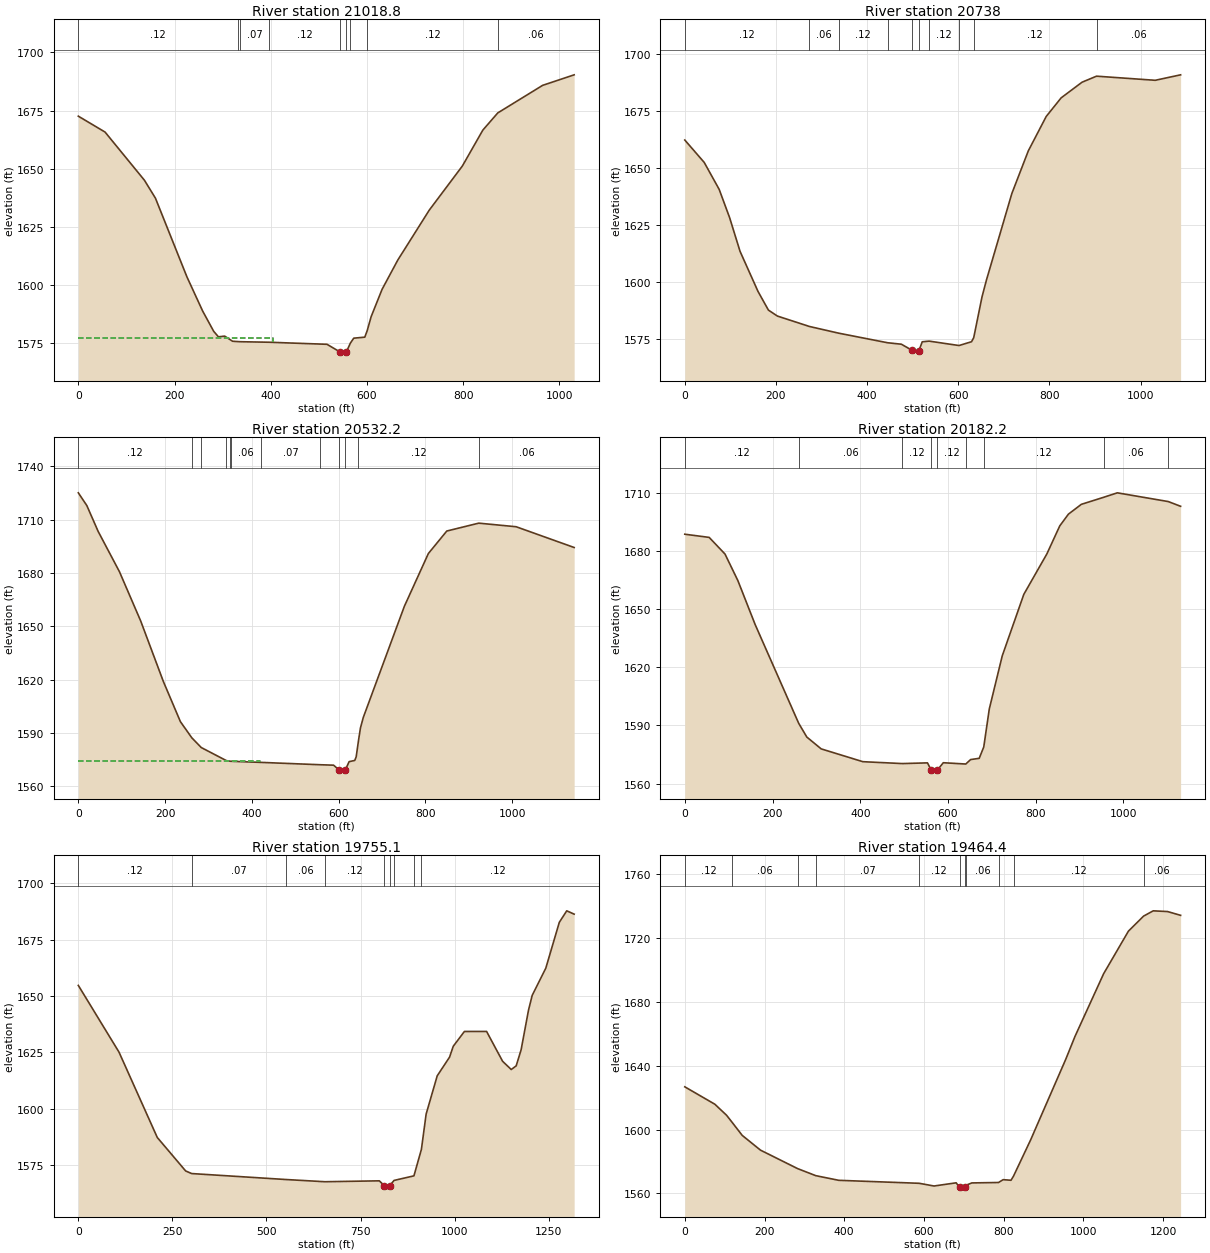
Type RM Length L Ch R = 1 ,21018.8 ,283.4,280.8,277.9
XS GIS Cut Line= 2
     2056460.606      238739.969     2057469.287      238951.774
#Sta/Elev= 30
       0 1672.57    55.6 1665.73   137.4 1645.04   160.3 1637.33   225.8 1603.49
   258.5 1588.81   281.4 1580.11   291.2 1577.75   304.3 1578.04   320.7 1575.84
  331.921575.698   336.71575.643  396.84 1575.42     517 1574.53   543.2 1571.33
     553 1570.74  557.431571.361  565.681575.103   572.6 1577.17   595.5  1577.6
  600.551580.431   608.6 1586.35   631.5 1598.19   664.2 1610.78   729.6 1632.22
   798.4 1651.18   840.9 1666.59  871.971673.977   965.2 1685.82  1030.7 1690.34
#Mann= 9 ,-1 , 0
       0     .12       0  331.92     .06       0   336.7     .07       0
  396.84     .12       0   543.2    .045       0  557.43     .12       0
  565.68    .016       0  600.55     .12       0  871.97     .06       0
#XS Ineff= 2 , 0
          404.27 1577.12
Permanent Ineff=
       F       F
Bank Sta=543.2,557.43
XS Rating Curve= 0 ,0
Exp/Cntr=0.3,0.1

Type RM Length L Ch R = 1 ,20738   ,209.6,205.8,205.9
XS GIS Cut Line= 2
     2056373.801      239017.747     2057451.926       239163.58
#Sta/Elev= 30
       0 1662.34    42.6 1652.52    75.4 1640.71    98.3 1628.32   121.2 1613.52
   160.6 1595.94   183.5 1587.72   203.2 1585.11  273.521580.542  337.821577.595
  445.06  1573.4   475.2 1572.76   498.8 1570.08   511.2 1568.85   513.8 1569.98
     521 1573.82  536.111574.117  601.661572.182   629.2 1573.86  633.951575.648
   652.1  1593.5   661.9 1600.95   717.6 1638.88   753.7 1657.58     793 1672.68
   825.8 1680.85   871.7 1687.72  903.361690.359  1032.2 1688.55  1087.9 1690.95
#Mann= 10 ,-1 , 0
       0     .12       0  273.52     .06       0  337.82     .12       0
  445.06     .07       0   498.8    .045       0   513.8     .07       0
  536.11     .12       0  601.66    .016       0  633.95     .12       0
  903.36     .06       0
Bank Sta=498.8,513.8
XS Rating Curve= 0 ,0
Exp/Cntr=0.3,0.1

Type RM Length L Ch R = 1 ,20532.2 ,343.5,350,340.1
XS GIS Cut Line= 3
      2056323.61      239278.315     2056929.279      239227.999
     2057450.278      239349.479
#Sta/Elev= 30
       0  1725.1    19.6 1717.93    45.7 1703.39    94.8 1680.71   143.8 1652.96
     196 1618.93   235.3 1596.34  261.591587.267  283.261581.809  341.251574.428
  348.861574.133   351.61574.062  419.88 1573.46  557.77 1572.12   588.2 1571.88
   600.3 1569.35     611 1568.53   615.3  1569.2   624.1 1573.86   637.1 1574.54
   640.4 1576.63  645.631585.649   650.2 1592.83   656.7 1598.72   751.3  1661.2
   806.7 1690.95   849.2 1703.61  922.831708.039    1009 1706.02  1142.7 1694.34
#Mann= 12 ,-1 , 0
       0     .12       0  261.59     .06       0  283.26     .12       0
  341.25     .06       0  348.86     .12       0   351.6     .06       0
  419.88     .07       0  557.77     .12       0   600.3    .045       0
   615.3    .016       0  645.63     .12       0  922.83     .06       0
#XS Ineff= 2 , 0
          418.05 1574.42
Permanent Ineff=
       F       F
Bank Sta=600.3,615.3
XS Rating Curve= 0 ,0
Exp/Cntr=0.3,0.1

Type RM Length L Ch R = 1 ,20182.2 ,416.7,427.1,440.5
XS GIS Cut Line= 3
     2056314.099      239496.638     2056881.633      239544.931
     2057438.082      239475.374
#Sta/Elev= 30
       0 1688.66    55.6 1687.02    91.7 1678.42   121.1 1664.69   160.4 1642.07
  259.631591.149   278.2 1584.03     311 1577.93   405.9 1571.33  496.151570.353
   553.2 1570.72  561.471567.166   566.3 1566.46   576.1 1567.08   589.3 1570.79
   640.61570.123   651.6 1572.42   671.2 1573.06  681.591578.918   694.2 1598.52
   723.7 1625.89   772.9 1657.64   825.4 1678.47   854.9 1692.97   874.6 1699.01
   904.1 1704.08  954.631707.683   986.1 1710.01 1102.241705.504  1130.4 1703.06
#Mann= 9 ,-1 , 0
       0     .12       0  259.63     .06       0  496.15     .12       0
  561.47    .045       0   576.1     .12       0   640.6    .016       0
  681.59     .12       0  954.63     .06       0 1102.24     .08       0
Bank Sta=561.47,576.1
XS Rating Curve= 0 ,0
Exp/Cntr=0.3,0.1

Type RM Length L Ch R = 1 ,19755.1 ,286.7,290.8,293.2
XS GIS Cut Line= 2
      2056302.62      239548.997      2057458.87      240180.941
#Sta/Elev= 30
       0 1654.67   108.2 1625.06   209.8 1587.25   285.2  1572.4  301.141571.244
     5521568.596  655.221567.619   799.8 1568.02   812.9 1565.94   819.4 1564.34
  827.53 1565.92   839.1  1568.2  891.881570.229  911.781581.986   924.3  1597.6
   953.8 1614.59   986.6 1622.88   996.4 1627.69    1026 1634.25    1085 1634.26
  1127.6 1621.02  1150.5 1617.38  1163.6    1619  1176.7 1626.09  1196.4 1643.71
  1206.2 1650.27  1242.3 1662.31  1278.3 1682.67    1298 1687.75  1317.7 1686.28
#Mann= 9 ,-1 , 0
       0     .12       0  301.14     .07       0     552     .06       0
  655.22     .12       0   812.9    .045       0  827.53     .12       0
   839.1    .016       0  891.88     .08       0  911.78     .12       0
Bank Sta=812.9,827.53
XS Rating Curve= 0 ,0
Exp/Cntr=0.3,0.1

Type RM Length L Ch R = 1 ,19464.4 ,299.4,303.3,305.1
XS GIS Cut Line= 2
     2056248.801      239639.275     2057227.967      240406.636
#Sta/Elev= 30
       0  1626.7    75.3 1615.83   104.8 1608.92  119.061604.397     144 1596.35
   189.9 1587.11  283.271575.533  328.631571.151   386.3 1568.24  588.071566.378
   625.3 1564.68   680.9 1566.68   689.3 1563.79   697.3 1562.73   703.9    1564
  706.511565.256   720.2 1566.61  787.061566.875   798.8 1568.65   818.4 1568.27
  824.741570.863   867.6 1593.46   955.9 1643.97   978.9 1658.18  1050.9 1697.45
  1113.1 1724.06 1151.151733.457  1175.3 1736.75  1211.3 1736.29    1244 1733.93
#Mann= 11 ,-1 , 0
       0     .12       0  119.06     .06       0  283.27     .12       0
  328.63     .07       0  588.07     .12       0   689.3    .045       0
   703.9     .12       0  706.51     .06       0  787.06    .016       0
  824.74     .12       0 1151.15     .06       0
Bank Sta=689.3,703.9
XS Rating Curve= 0 ,0
Exp/Cntr=0.3,0.1