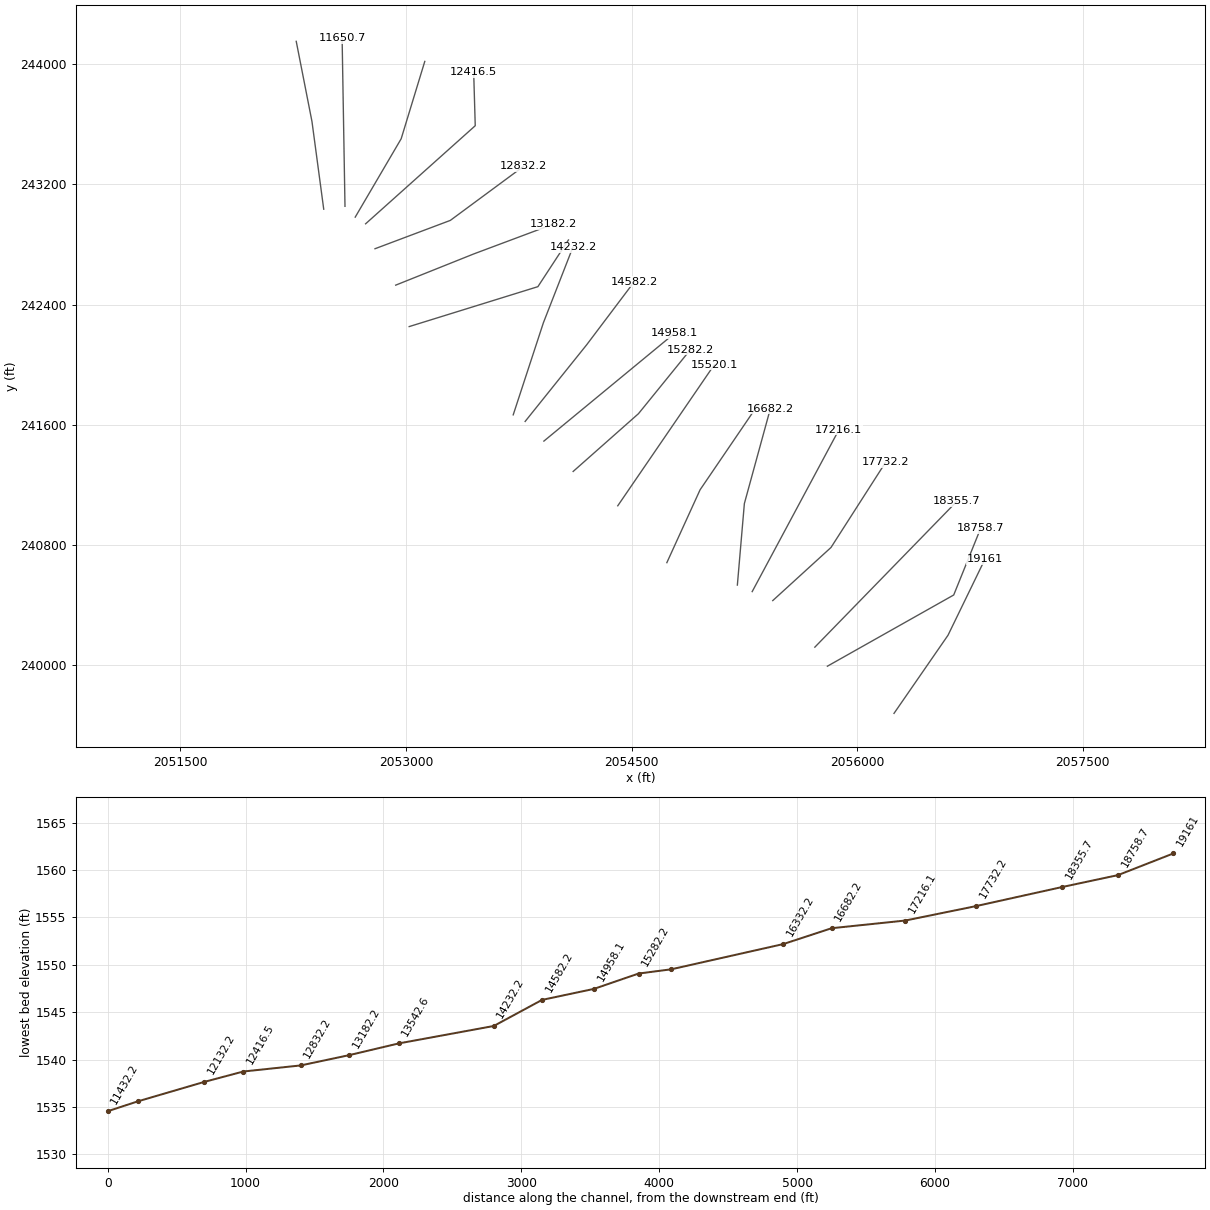
HEC-RAS study KELLYCK.prj: KELLYCK

--- KELLYCK.g01 (geometry) --- (continued)

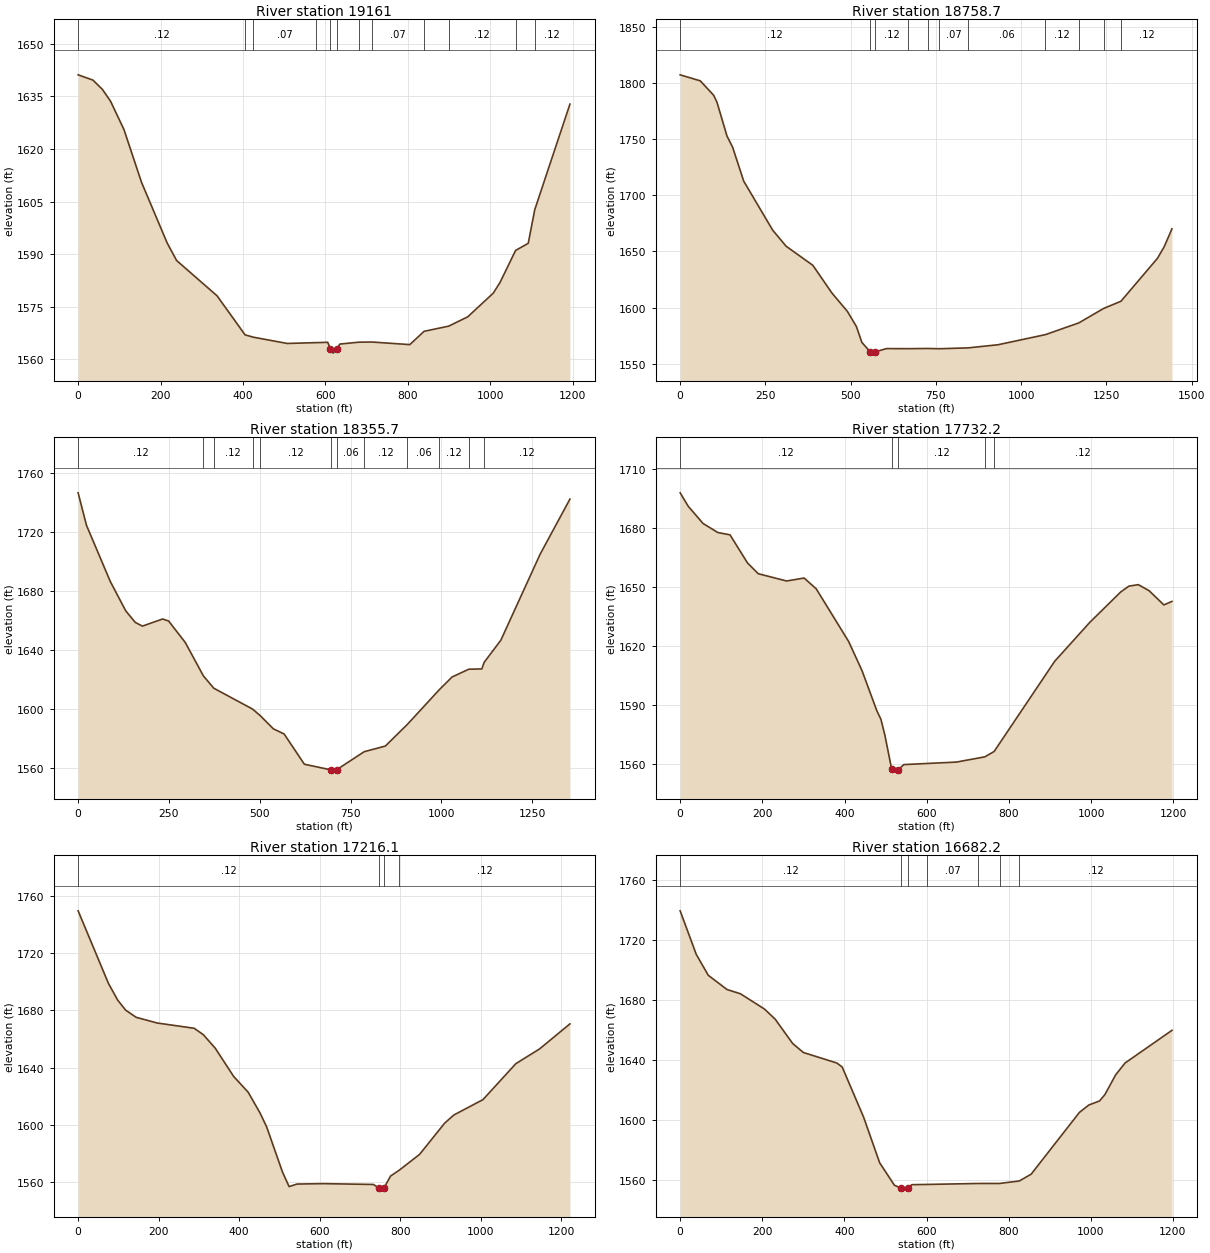
Type RM Length L Ch R = 1 ,19161   ,409.8,402.3,389.3
XS GIS Cut Line= 3
     2056245.821      239679.504     2056604.818      240199.244
     2056849.997      240704.231
#Sta/Elev= 30
       0 1641.17      36 1639.66    58.9 1637.01    78.6 1633.65   111.3 1625.52
   153.8 1610.49     216 1593.19   238.9 1588.18   337.1  1578.1  405.021566.958
  425.341566.291   507.3 1564.51  576.331564.741   605.5 1564.84     612 1562.93
   618.6 1561.75  627.471562.907   634.9 1564.34  680.451564.869  712.821564.919
   804.6 1564.18  839.18 1567.97  898.911569.452     945  1572.1    1007 1578.86
  1023.3 1581.88 1061.251591.056  1091.9 1593.09 1107.671602.676    1193 1632.81
#Mann= 12 ,-1 , 0
       0     .12       0  405.02     .06       0  425.34     .07       0
  576.33     .12       0     612    .045       0  627.47     .12       0
  680.45     .06       0  712.82     .07       0  839.18     .06       0
  898.91     .12       0 1061.25    .016       0 1107.67     .12       0
Bank Sta=612,627.47
XS Rating Curve= 0 ,0
Exp/Cntr=0.3,0.1

Type RM Length L Ch R = 1 ,18758.7 ,394.9,403,408.9
XS GIS Cut Line= 3
      2055802.62      239993.441     2056642.898        240467.4
     2056821.717      240910.108
#Sta/Elev= 30
       0  1807.2    58.9 1801.87    98.1 1789.07   107.9 1782.88   137.4 1752.65
   153.7 1742.89   186.4 1712.56   271.4  1668.9   310.7 1654.64   389.2 1637.61
   444.8 1613.08   490.5 1596.57   516.7 1583.24     533 1568.95   557.41560.609
   565.8 1559.46   572.3 1560.63     605  1563.5  669.011563.426  726.481563.602
  760.391563.377   844.41564.125     932 1566.92 1071.041575.916 1168.981586.356
 1242.241599.283 1292.64 1605.63  1399.7 1643.86  1419.3 1654.08  1442.2 1670.11
#Mann= 11 ,-1 , 0
       0     .12       0   557.4    .045       0   572.3     .12       0
  669.01     .06       0  726.48     .12       0  760.39     .07       0
   844.4     .06       0 1071.04     .12       0 1168.98     .06       0
 1242.24    .016       0 1292.64     .12       0
Bank Sta=557.4,572.3
XS Rating Curve= 0 ,0
Exp/Cntr=0.3,0.1

Type RM Length L Ch R = 1 ,18355.7 ,622.4,623.5,623
XS GIS Cut Line= 2
     2055719.287      240120.177     2056663.731      241090.664
#Sta/Elev= 30
       0 1746.28      23 1724.34    88.5 1686.41   131.2 1666.49   157.4  1658.7
   177.1 1656.21   232.8 1661.02   249.2 1659.65   295.1 1645.12  344.931622.569
  373.451614.257  480.521600.118  501.971595.587   537.7 1586.78   567.2 1583.33
     623 1562.87  696.13 1559.08   701.7 1558.21   711.5 1559.09  787.531571.315
     846 1575.16  906.94 1589.88  994.771613.295  1029.6  1621.8 1075.711627.087
  1111.6 1627.27 1118.151631.771    1164 1646.68  1272.2  1704.8  1354.2 1742.04
#Mann= 12 ,-1 , 0
       0     .12       0  344.93     .06       0  373.45     .12       0
  480.52     .06       0  501.97     .12       0  696.13    .045       0
   711.5     .06       0  787.53     .12       0  906.94     .06       0
  994.77     .12       0 1075.71    .016       0 1118.15     .12       0
Bank Sta=696.13,711.5
XS Rating Curve= 0 ,0
Exp/Cntr=0.3,0.1

Type RM Length L Ch R = 1 ,17732.2 ,499.5,516.1,514.4
XS GIS Cut Line= 3
     2055439.363      240430.126     2055826.792      240783.707
     2056189.278      241349.534
#Sta/Elev= 30
       0 1697.81    19.7 1690.96    55.7 1682.22    91.8  1677.6   121.3 1676.44
   163.9 1662.11   190.1 1656.65     259 1652.95   301.6 1654.45   331.1 1648.95
   409.8 1622.21   442.6 1607.26   478.6 1586.87   488.5 1582.55   498.3  1574.3
   514.7 1557.06   521.2  1556.2   531.1    1557   544.2 1559.53     672  1560.8
  741.391563.472  763.921566.207   911.3 1612.12   996.5 1631.87  1071.9 1647.38
  1091.6 1650.31  1114.6 1651.09  1140.8 1648.02  1176.8 1640.78  1196.5 1642.55
#Mann= 5 ,-1 , 0
       0     .12       0   514.7    .045       0   531.1     .12       0
  741.39     .06       0  763.92     .12       0
Bank Sta=514.7,531.1
XS Rating Curve= 0 ,0
Exp/Cntr=0.3,0.1

Type RM Length L Ch R = 1 ,17216.1 ,522.8,533.9,536.5
XS GIS Cut Line= 2
      2055302.62      240489.969     2055879.009      241566.358
#Sta/Elev= 30
       0 1749.92    75.3 1698.98    98.2  1687.3   117.8 1680.29     144 1675.22
   196.4 1671.21   288.1 1667.53     311 1662.99   340.4 1653.55   386.3 1633.69
   422.3 1622.62   451.7 1608.06   468.1  1598.3   507.4 1566.64   523.8 1556.45
   543.4 1558.23   608.9 1558.52   733.2 1557.94   746.4 1555.54   756.2 1554.67
  759.811555.695   775.8 1563.87  797.21 1567.95   847.8 1579.06     910 1600.97
   932.9 1606.69    1005 1617.44  1086.8  1642.7  1145.7 1653.05    1221  1670.6
#Mann= 4 ,-1 , 0
       0     .12       0   746.4    .045       0  759.81     .06       0
  797.21     .12       0
Bank Sta=746.4,759.81
XS Rating Curve= 0 ,0
Exp/Cntr=0.3,0.1

Type RM Length L Ch R = 1 ,16682.2 ,355.5,350,341.4
XS GIS Cut Line= 3
     2055203.951      240533.474     2055250.589      241076.105
     2055423.055      241705.964
#Sta/Elev= 30
       0  1739.2    39.1 1710.26    68.5 1696.27   114.1 1686.79   146.8 1683.97
   205.5 1673.77   231.6 1666.98     274 1650.84     300 1644.87   381.6 1637.84
   394.6 1635.21   446.8 1601.78   485.9 1571.39   521.8 1556.46   538.1 1554.51
   544.6 1553.86   554.4 1554.59   564.2 1556.82  601.151556.982   725.4 1557.62
  777.781557.638   825.91559.279   854.8 1563.81   972.4 1604.97   995.2 1609.87
  1021.4  1612.6  1034.4 1616.81  1060.5  1629.9  1083.4 1637.83  1197.7 1659.61
#Mann= 7 ,-1 , 0
       0     .12       0   538.1    .045       0   554.4     .12       0
  601.15     .07       0   725.4     .12       0  777.78     .06       0
   825.9     .12       0
Bank Sta=538.1,554.4
XS Rating Curve= 0 ,0
Exp/Cntr=0.3,0.1

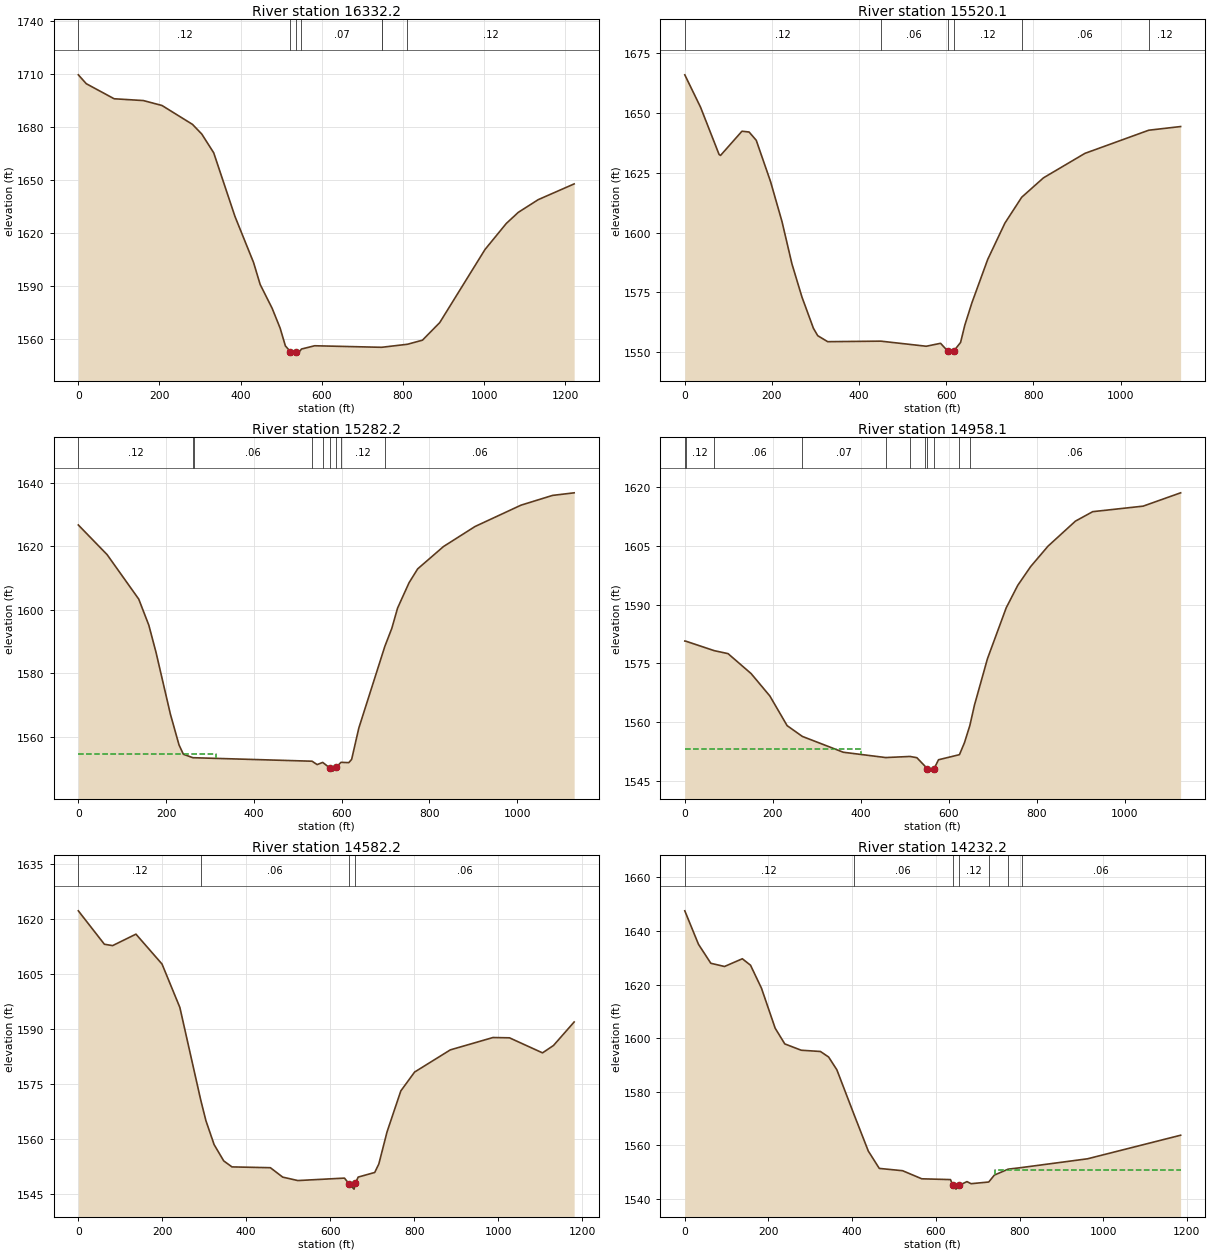
Type RM Length L Ch R = 1 ,16332.2 ,812.9,812,641.6
XS GIS Cut Line= 3
     2054734.991      240682.581     2054956.119      241167.752
     2055343.536      241737.048
#Sta/Elev= 30
       0 1709.71    19.6 1704.68    88.3 1696.16   160.3 1695.14   206.1 1692.36
   281.3 1681.66   304.2 1676.19   333.6 1665.58     386 1629.54   431.8 1603.48
   448.1 1591.04   477.6 1577.56   497.2 1566.38   510.3 1556.26  522.791552.961
   526.6 1552.19   536.5 1552.94     543 1552.48   549.91554.514   582.4 1556.36
  747.331555.484  747.521555.491  811.071557.207     848 1559.52   890.6 1569.48
  1002.1 1610.84  1054.6 1625.59  1084.1 1631.86  1133.3 1639.06  1221.8 1647.97
#Mann= 7 ,-1 , 0
       0     .12       0  522.79    .045       0   536.5     .12       0
   549.9     .07       0  747.33     .12       0  747.52     .06       0
  811.07     .12       0
Bank Sta=522.79,536.5
XS Rating Curve= 0 ,0
Exp/Cntr=0.3,0.1

Type RM Length L Ch R = 1 ,15520.1 ,243,238,234.8
XS GIS Cut Line= 2
     2054408.523       241061.15     2055050.884      242000.386
#Sta/Elev= 30
       0 1665.98    36.1 1652.45    78.7 1632.65      82 1632.25   131.2 1642.38
   147.6 1642.05     164 1638.58   196.8 1621.31     223 1604.63   245.9 1586.86
   268.9 1572.99   295.1 1559.96     305 1556.84   327.9 1554.32  449.891554.541
   554.2 1552.41     587 1553.64   603.4  1550.4   609.9 1549.53   617.3 1550.41
   632.9    1554   642.7 1561.27   659.1 1570.69   695.2 1588.75   734.6 1603.92
  773.191614.755   823.1 1622.87   918.2 1633.11 1064.781642.803  1137.9 1644.34
#Mann= 6 ,-1 , 0
       0     .12       0  449.89     .06       0   603.4    .045       0
   617.3     .12       0  773.19     .06       0 1064.78     .12       0
Bank Sta=603.4,617.3
XS Rating Curve= 0 ,0
Exp/Cntr=0.3,0.1

Type RM Length L Ch R = 1 ,15282.2 ,324.8,324.1,309.9
XS GIS Cut Line= 3
     2054111.831       241289.61     2054546.381      241674.293
     2054892.487      242101.268
#Sta/Elev= 30
       0 1626.74    65.6 1617.39   137.7 1603.35   160.7 1595.11   177.1 1586.53
   209.8 1567.07   229.5 1557.34   239.4  1554.4   261.71553.282  263.111553.309
  532.661552.208   544.3 1551.14   556.91551.832   572.9 1550.11   580.4 1549.08
   586.9 1550.23  598.621551.853   616.4 1551.76   622.9 1552.79   639.2 1562.65
   698.61588.467   714.5 1594.16   727.6 1600.54   753.8 1608.54   773.4  1612.9
   832.3 1619.95   904.2 1626.27  1008.9    1633  1080.9 1636.08    1130 1636.89
#Mann= 9 ,-1 , 0
       0     .12       0   261.7     .07       0  263.11     .06       0
  532.66     .12       0   556.9     .06       0   572.9    .045       0
   586.9     .06       0  598.62     .12       0   698.6     .06       0
#XS Ineff= 2 , 0
          314.29 1554.57
Permanent Ineff=
       F       F
Bank Sta=572.9,586.9
XS Rating Curve= 0 ,0
Exp/Cntr=0.3,0.1

Type RM Length L Ch R = 1 ,14958.1 ,369.3,375.9,379.6
XS GIS Cut Line= 2
     2053917.203      241491.705     2054786.331      242208.997
#Sta/Elev= 30
       0 1580.67    2.271580.642   67.021578.216    98.3 1577.46   150.7 1572.37
   193.3 1566.65   232.6 1559.07  267.251556.318   360.3 1552.28  456.741550.924
  511.881551.205   527.4 1550.89  545.761548.746   550.3    1548   560.2 1547.46
   566.7  1548.1   576.6 1550.36  624.211551.664   635.5 1554.68   647.81559.085
   658.4 1564.34   687.9 1576.17   730.5 1589.16   756.7 1594.89   786.2 1599.71
   825.5  1604.9   887.8 1611.29   927.1 1613.71  1041.7 1615.12  1126.9 1618.52
#Mann= 11 ,-1 , 0
       0     .06       0    2.27     .12       0   67.02     .06       0
  267.25     .07       0  456.74     .06       0  511.88     .12       0
  545.76     .06       0   550.3    .045       0   566.7     .06       0
  624.21     .12       0   647.8     .06       0
#XS Ineff= 2 , 0
          400.33 1553.03
Permanent Ineff=
       F       F
Bank Sta=550.3,566.7
XS Rating Curve= 0 ,0
Exp/Cntr=0.3,0.1

Type RM Length L Ch R = 1 ,14582.2 ,340.7,350,353
XS GIS Cut Line= 3
     2053792.515      241622.511     2054201.564      242132.437
     2054519.146      242553.811
#Sta/Elev= 30
       0  1622.3    62.1 1613.17    81.7  1612.8   137.3 1615.93   199.4 1607.77
   241.9 1595.92  291.471570.725     304 1564.99   323.6 1558.44   346.5    1554
   366.1 1552.37   457.6 1552.15     487 1549.58     523 1548.64   634.1 1549.31
  644.961547.768     657  1546.3  659.971547.866   666.8 1549.59   706.2 1550.85
     716 1553.17   735.6 1561.95   768.4 1573.12   801.2 1578.27   886.4 1584.33
     988  1587.7  1027.3 1587.62    1106 1583.51  1132.2 1585.53  1181.4 1591.95
#Mann= 4 ,-1 , 0
       0     .12       0  291.47     .06       0  644.96    .045       0
  659.97     .06       0
Bank Sta=644.96,659.97
XS Rating Curve= 0 ,0
Exp/Cntr=0.3,0.1

Type RM Length L Ch R = 1 ,14232.2 ,702.9,689.6,665.4
XS GIS Cut Line= 3
     2053713.134      241666.342     2053913.828      242279.173
     2054110.104      242782.291
#Sta/Elev= 30
       0 1647.54    32.7 1635.04    62.2 1627.94    94.9 1626.74   137.5 1629.63
   157.1 1627.21   183.3  1618.6     216 1603.67     239 1597.81   278.2 1595.45
   324.1 1594.98   343.7 1592.92   363.4 1588.14  403.741571.707   438.6 1557.76
   464.8 1551.29   520.5 1550.43   566.3 1547.41     635 1547.11  640.22 1545.01
   648.1 1543.55  656.371545.023   674.3 1546.36   684.1 1545.58  726.41 1546.21
   739.8  1548.8  772.771551.011  804.75 1551.61   962.3 1554.88  1184.9 1563.69
#Mann= 7 ,-1 , 0
       0     .12       0  403.74     .06       0  640.22    .045       0
  656.37     .12       0  726.41     .06       0  772.77     .12       0
  804.75     .06       0
#XS Ineff= 2 , 0
                           740.7         1550.63
Permanent Ineff=
       F       F
Bank Sta=640.22,656.37
XS Rating Curve= 0 ,0
Exp/Cntr=0.3,0.1

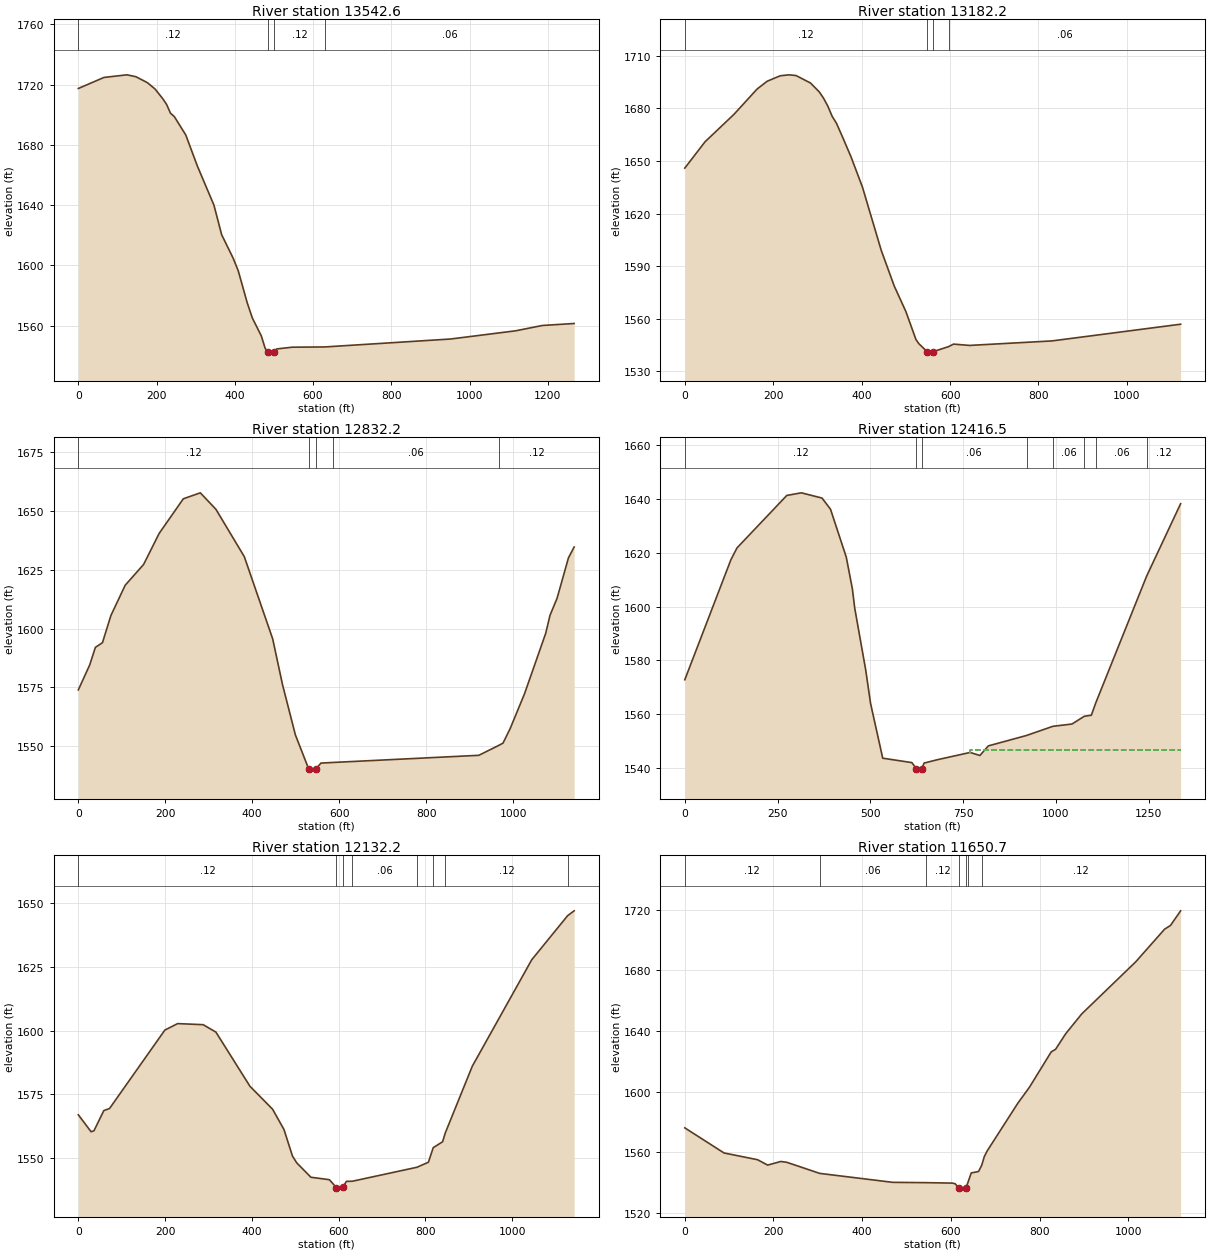
Type RM Length L Ch R = 1 ,13542.6 ,356.7,360.4,360.3
XS GIS Cut Line= 3
      2053021.37      242253.858     2053877.273      242519.483
     2054080.398      242830.247
#Sta/Elev= 30
       0 1717.43    65.4 1724.76   124.3  1726.5   147.2 1725.24   176.6 1721.29
   196.2 1717.06   215.9 1710.61   225.7 1706.82   235.5 1701.05   245.3  1698.8
   274.7 1686.54   304.2 1665.98   346.7 1639.94   366.3 1620.38   395.8 1604.74
   408.8 1596.36   431.7 1575.14   444.8 1565.04   467.7 1553.18   477.5 1544.94
   484.1 1542.53   493.9 1541.71   500.4 1542.48     507 1544.48   546.2 1545.64
  630.26 1545.82   951.5 1551.08  1117.6 1556.52    1186 1560.06  1267.4 1561.39
#Mann= 4 ,-1 , 0
       0     .12       0   484.1    .045       0   500.4     .12       0
  630.26     .06       0
Bank Sta=484.1,500.4
XS Rating Curve= 0 ,0
Exp/Cntr=0.3,0.1

Type RM Length L Ch R = 1 ,13182.2 ,347.7,350,353.2
XS GIS Cut Line= 3
     2052931.609      242529.615     2053450.399      242737.243
     2053977.333      242934.562
#Sta/Elev= 30
       0 1645.92    45.8 1660.92   111.1 1676.53   163.4 1690.94   186.3 1695.42
   215.7 1698.52   235.3 1699.08   251.6 1698.67   284.3 1694.42   303.9 1689.43
   313.7 1685.82   323.5 1681.26   333.3 1675.44   343.1 1671.45   356.2 1663.99
   375.8 1652.45   401.9 1635.05   444.4 1598.99   473.8 1578.67     500 1564.22
   522.8 1548.26   529.4 1545.85  548.041541.353   555.5 1540.47   562.1 1541.34
  596.49 1544.16   607.9 1545.61   643.8 1544.86   830.3 1547.42  1121.5 1556.95
#Mann= 4 ,-1 , 0
       0     .12       0  548.04    .045       0   562.1     .12       0
  596.49     .06       0
Bank Sta=548.04,562.1
XS Rating Curve= 0 ,0
Exp/Cntr=0.3,0.1

Type RM Length L Ch R = 1 ,12832.2 ,405.5,415.7,416.4
XS GIS Cut Line= 3
     2052793.942      242771.982      2053294.81      242960.496
     2053781.781      243320.273
#Sta/Elev= 30
       0 1573.92    26.1 1584.49    39.2 1591.98    55.5 1593.99      75 1605.55
   107.7 1618.37   150.1 1627.21     186 1640.44   241.5 1655.13   280.6 1657.67
   316.5 1650.68   381.8 1630.55   447.1  1595.6   469.9 1576.01   499.3 1554.81
  530.391540.084   541.7 1539.39  546.111540.257   558.1  1542.8  586.331543.075
   921.4 1546.11  968.591550.458     977 1551.31   993.4 1557.48  1026.1 1572.11
  1075.2 1597.98    1085 1605.58  1101.4 1612.92  1127.5 1630.05  1140.6 1634.64
#Mann= 5 ,-1 , 0
       0     .12       0  530.39    .045       0  546.11     .12       0
  586.33     .06       0  968.59     .12       0
Bank Sta=530.39,546.11
XS Rating Curve= 0 ,0
Exp/Cntr=0.3,0.1

Type RM Length L Ch R = 1 ,12416.5 ,280.9,284.3,296.6
XS GIS Cut Line= 3
      2052731.44      242937.886     2053460.606      243590.663
      2053450.19      243948.303
#Sta/Elev= 30
       0 1572.76   124.4 1617.47   140.8 1621.84     275 1641.36   314.2 1642.33
   369.9 1640.38   392.8 1636.22   435.3 1618.38   451.7 1606.59   458.2 1599.31
   487.7 1576.37   500.8 1563.92   533.5 1543.57   612.1 1541.92   624.3 1539.64
   628.4 1538.75   639.3 1539.65   644.8 1541.74   680.8    1543   769.2  1545.7
   795.4 1544.57   818.3 1548.15   921.11552.016  992.161555.429  1043.7 1556.28
  1076.8 1559.16  1095.8 1559.55 1108.311564.333 1244.971611.351  1336.5 1638.28
#Mann= 8 ,-1 , 0
       0     .12       0   624.3    .045       0   639.3     .06       0
   921.1     .12       0  992.16     .06       0  1076.8    .016       0
 1108.31     .06       0 1244.97     .12       0
#XS Ineff= 2 , 0
                          767.79         1546.62
Permanent Ineff=
       F       F
Bank Sta=624.3,639.3
XS Rating Curve= 0 ,0
Exp/Cntr=0.3,0.1

Type RM Length L Ch R = 1 ,12132.2 ,461.8,481.5,485.5
XS GIS Cut Line= 3
     2052662.291      242982.204     2052968.024      243503.949
     2053124.973      244018.636
#Sta/Elev= 30
       0 1566.87    29.4 1560.21      36 1560.58    58.8 1568.53    71.9 1569.33
   199.4 1600.16   228.8 1602.71   287.6 1602.29   317.1 1599.37   395.5  1578.1
   447.8 1569.05     474 1561.07   493.6 1550.64   503.4 1547.98   536.1 1542.32
   578.6 1541.36   594.9 1538.26   604.7 1537.65  609.791538.323   617.8  1540.7
  631.611540.751  780.421546.241   806.9 1548.22  817.971553.947   839.5 1556.26
  845.861559.763     908 1585.95    1045 1627.79 1127.761645.134  1142.8 1647.04
#Mann= 8 ,-1 , 0
       0     .12       0   594.9    .045       0  609.79     .12       0
  631.61     .06       0  780.42     .12       0  817.97    .016       0
  845.86     .12       0 1127.76     .06       0
Bank Sta=594.9,609.79
XS Rating Curve= 0 ,0
Exp/Cntr=0.3,0.1

Type RM Length L Ch R = 1 ,11650.7 ,215,218.5,221.7
XS GIS Cut Line= 2
     2052594.287      243054.205      2052575.19      244172.261
#Sta/Elev= 30
       0 1576.03    88.5 1559.46     164 1555.02   186.9 1551.46   216.4 1553.84
   229.6 1553.34  304.311545.988   468.9 1540.08  545.071539.863   603.4 1539.58
   609.9 1539.12  618.271536.188     623  1535.6  633.541536.232  637.981539.521
     646  1546.3   662.4 1547.21  669.47 1551.24   675.5  1557.1   682.1 1560.87
   750.9 1592.23   777.2 1602.81   826.4 1626.19   836.2 1627.89   859.2 1638.22
   895.2 1651.24  1016.6 1685.51  1082.2  1707.2  1095.3 1709.61  1118.2 1719.27
#Mann= 7 ,-1 , 0
       0     .12       0  304.31     .06       0  545.07     .12       0
  618.27    .045       0  633.54     .12       0  637.98    .016       0
  669.47     .12       0
Bank Sta=618.27,633.54
XS Rating Curve= 0 ,0
Exp/Cntr=0.3,0.1

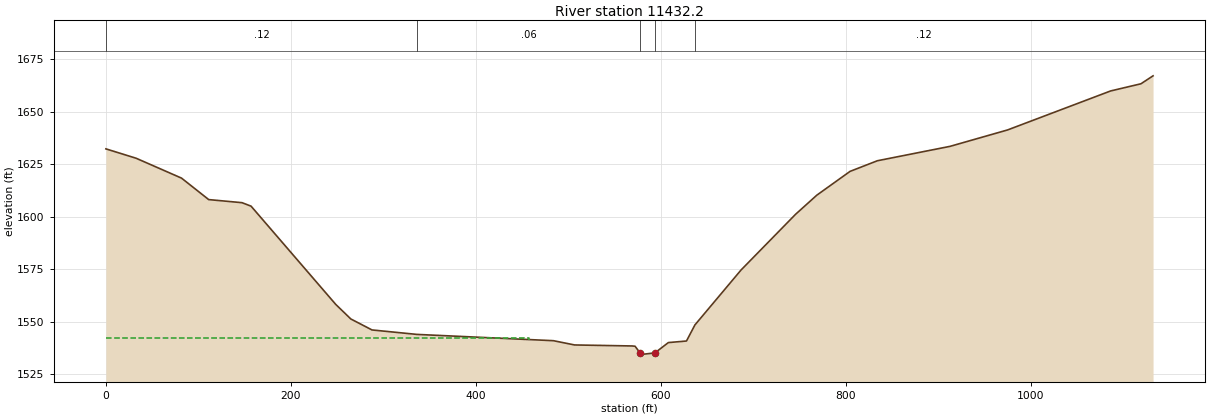
Type RM Length L Ch R = 1 ,11432.2 ,280.1,269.6,256
XS GIS Cut Line= 3
     2052452.859      243035.175     2052374.708      243618.589
     2052270.008      244152.259
#Sta/Elev= 30
       0 1632.36    32.7 1627.89    81.8 1618.42   111.2 1608.19   147.2 1606.72
     157 1605.06   248.5 1558.29   264.9 1551.31   287.8 1546.08  336.331543.959
     484 1540.96   506.9 1538.93     569 1538.45   572.3 1538.32   577.6 1535.18
   582.1 1534.56  593.741535.142   608.3 1540.06   627.9 1540.81  637.031548.472
   686.9 1574.63   745.9 1601.19   768.8 1610.27   804.8 1621.63   834.3 1626.69
     913 1633.56   975.2 1641.38  1086.6 1659.95  1119.4 1663.37  1132.5 1667.16
#Mann= 5 ,-1 , 0
       0     .12       0  336.33     .06       0   577.6    .045       0
  593.74    .016       0  637.03     .12       0
#XS Ineff= 2 , 0
          457.86 1542.38
Permanent Ineff=
       F       F
Bank Sta=577.6,593.74
XS Rating Curve= 0 ,0
Exp/Cntr=0.3,0.1