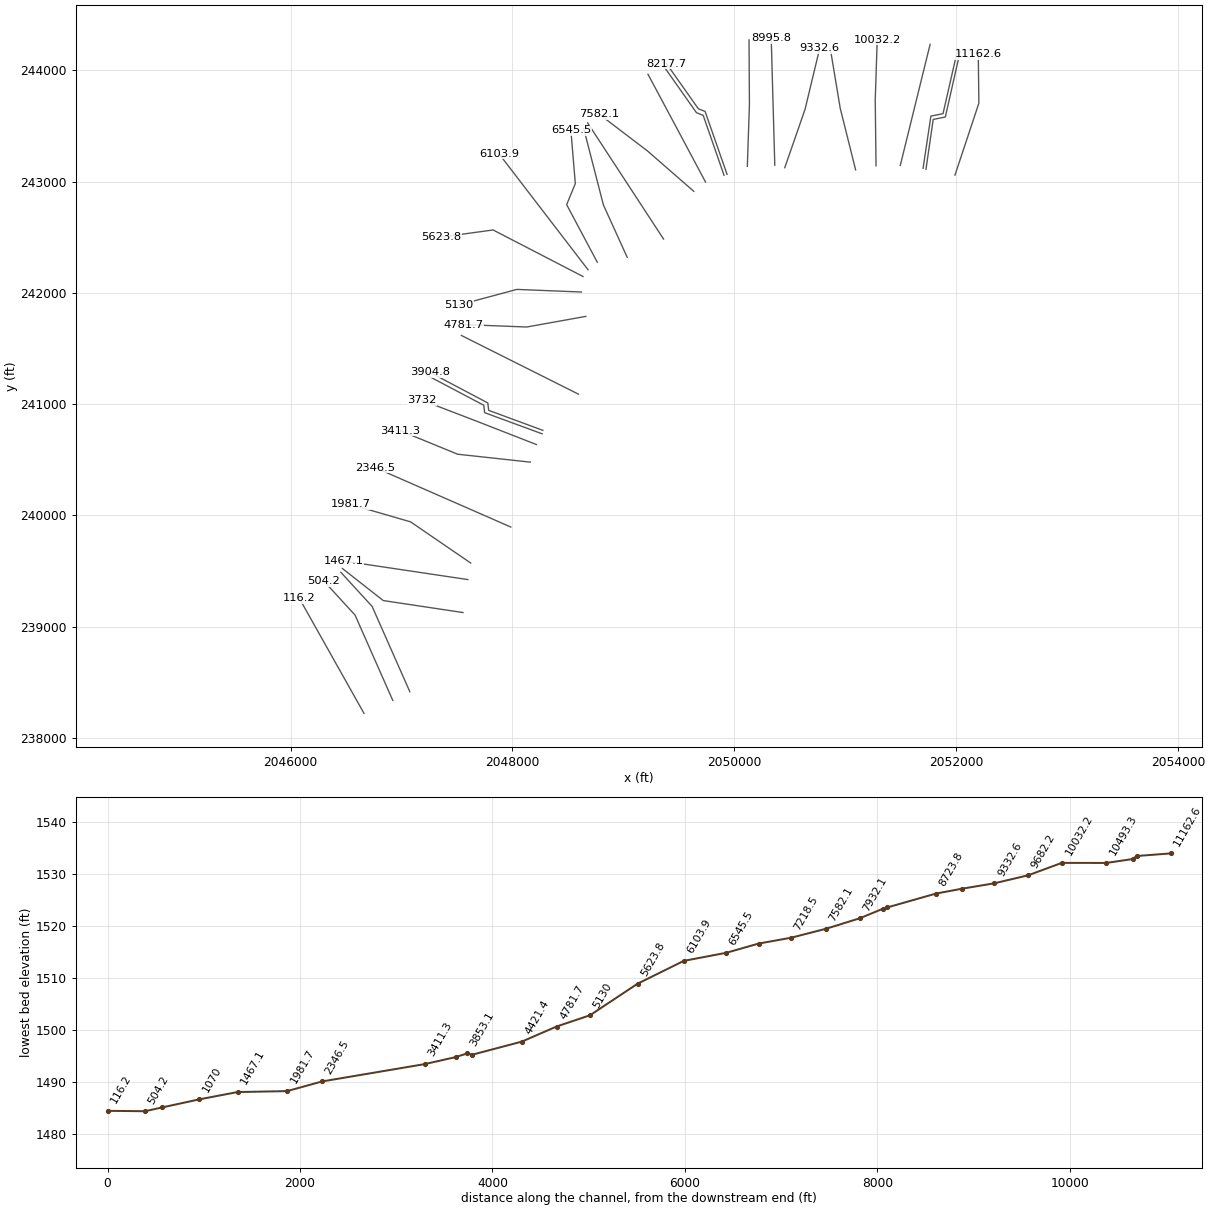
HEC-RAS study KELLYCK.prj: KELLYCK

--- KELLYCK.g01 (geometry) --- (continued)

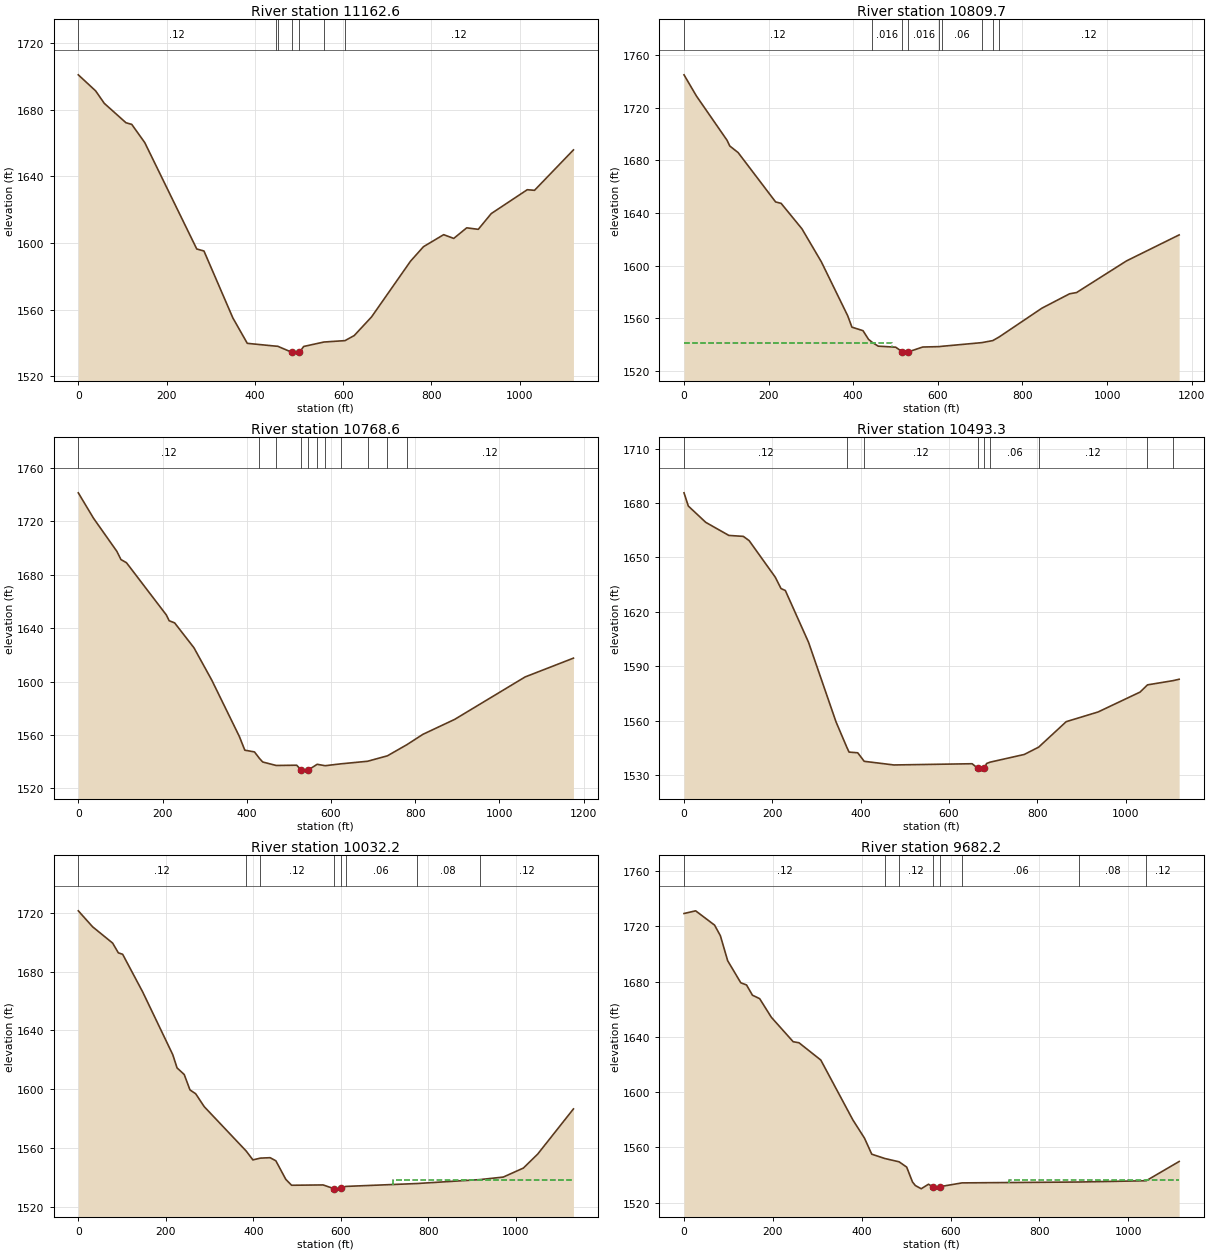
Type RM Length L Ch R = 1 ,11162.6 ,378.5,352.9,315.8
XS GIS Cut Line= 3
     2051988.384      243057.677     2052203.662      243703.511
     2052198.454      244144.483
#Sta/Elev= 30
       0 1701.03    39.3 1691.39    58.9  1683.9     108 1672.26   121.1 1671.28
   150.6 1660.33   268.4 1596.45   284.7 1595.25   350.2 1555.06   382.9  1539.8
  446.931538.135   451.51538.084   484.4 1534.38   494.2 1533.93  501.091534.352
   510.6 1537.93  556.711540.601  604.191541.437   625.1 1544.47   664.4 1555.67
   752.6  1589.1     782 1597.83   827.8 1605.06   850.6  1602.8     880 1609.16
   906.2 1608.26   935.6 1617.72  1017.2 1632.05  1033.6 1631.68  1121.8 1655.95
#Mann= 7 ,-1 , 0
       0     .12       0  446.93     .06       0   451.5     .12       0
   484.4    .045       0  501.09     .12       0  556.71    .016       0
  604.19     .12       0
Bank Sta=484.4,501.09
XS Rating Curve= 0 ,0
Exp/Cntr=0.3,0.1

Type RM Length L Ch R = 1 ,10809.7 ,38.5,41,51.3
XS GIS Cut Line= 4
     2051727.018      243109.933     2051792.122       243557.85
     2051901.497      243579.985     2052035.611      244171.131
#Sta/Elev= 30
       0 1745.05    29.5 1728.87   101.7  1695.3   108.2 1690.93   127.9 1685.93
   216.5 1648.41   229.6  1647.3   278.8 1627.94   324.7 1602.82     387  1561.8
   396.9 1553.18   423.1  1550.5   436.2 1543.89  445.421541.526     459 1538.74
   500.4 1537.94  515.491534.524   522.8 1533.43  530.111534.369   564.2 1538.07
  603.031538.373   609.71538.621   703.91541.411  729.781542.953   744.8 1545.69
     846 1567.61   911.5 1578.56   927.9 1579.49  1045.9 1603.55  1170.4 1623.33
#Mann= 9 ,-1 , 0
       0     .12       0  445.42    .016       0  515.49    .045       0
  530.11    .016       0  603.03     .12       0   609.7     .06       0
   703.9     .12       0  729.78     .06       0   744.8     .12       0
#XS Ineff= 2 , 0
          490.54 1540.84
Permanent Ineff=
       F       F
Bank Sta=515.49,530.11
XS Rating Curve= 0 ,0
Exp/Cntr=0.3,0.1

Type RM Length L Ch R = 1 ,10768.6 ,247.3,275.3,300.8
XS GIS Cut Line= 4
     2051700.976      243119.048     2051771.288      243587.798
     2051880.663      243609.933     2052012.173      244185.454
#Sta/Elev= 30
       0 1741.38      36 1722.41    91.5 1697.57   101.3 1691.38   114.4 1689.02
   209.2 1649.82   215.8 1645.55   228.8 1643.93   274.6 1625.32   317.1 1600.97
   382.5 1558.82   395.5 1548.54   418.4 1547.24  430.331542.342     438 1539.69
  470.041537.083   518.6 1537.28  530.02 1533.52   537.8 1532.85  545.481533.593
  567.291537.963  586.391536.911  623.131538.298  687.031540.241  734.181544.327
  780.221552.637   818.4 1560.42   893.9 1571.63  1061.2 1603.43  1175.9 1617.51
#Mann= 11 ,-1 , 0
       0     .12       0  430.33    .016       0  470.04     .12       0
  530.02    .045       0  545.48     .12       0  567.29    .016       0
  586.39     .12       0  623.13     .06       0  687.03     .12       0
  734.18     .06       0  780.22     .12       0
Bank Sta=530.02,545.48
XS Rating Curve= 0 ,0
Exp/Cntr=0.3,0.1

Type RM Length L Ch R = 1 ,10493.3 ,454.1,461.1,464.7
XS GIS Cut Line= 2
     2051495.329      243144.483     2051764.426      244233.025
#Sta/Elev= 30
       0 1685.67     9.8 1678.37    49.2 1669.39   101.6 1662.16   134.4 1661.64
   147.5  1659.3   206.6 1639.16   219.7 1632.86   229.5 1631.76     282  1603.2
   344.3 1559.25  368.85 1545.19   373.8  1542.6   393.4 1542.22   408.11537.514
   475.4  1535.5   652.5 1536.18   665.1  1533.7   672.1  1532.1   680.1 1533.63
   685.2 1536.29  693.111537.052   770.5 1541.29  803.071545.325   865.6  1559.4
   937.7 1564.74  1032.8 1575.72 1049.591579.699  1107.71582.038  1121.3  1582.8
#Mann= 9 ,-1 , 0
       0     .12       0  368.85    .016       0   408.1     .12       0
   665.1    .045       0   680.1     .12       0  693.11     .06       0
  803.07     .12       0 1049.59     .06       0  1107.7     .12       0
Bank Sta=665.1,680.1
XS Rating Curve= 0 ,0
Exp/Cntr=0.3,0.1

Type RM Length L Ch R = 1 ,10032.2 ,343.4,350,353.2
XS GIS Cut Line= 3
     2051276.749      243141.512     2051269.763      243733.796
     2051287.419      244273.158
#Sta/Elev= 30
       0  1721.3    32.7 1710.45    78.5 1699.37    91.6 1692.72   101.4 1691.77
   147.3  1666.1     216 1623.51   225.8 1614.52   242.2 1610.02   255.3 1599.58
   268.4 1596.93     288 1588.14  383.681558.061   399.2 1551.99  416.42 1553.19
   438.5 1553.48   451.6 1551.39   474.5 1538.72   487.6 1534.74   559.6 1534.96
   584.8 1532.41     589 1532.11   599.8 1532.56  611.411533.955  773.251535.901
  917.651538.568   971.7 1540.31  1017.5 1546.42  1050.2  1555.9    1132 1586.63
#Mann= 8 ,-1 , 0
       0     .12       0  383.68    .016       0  416.42     .12       0
   584.8    .045       0   599.8     .12       0  611.41     .06       0
  773.25     .08       0  917.65     .12       0
#XS Ineff= 2 , 0
                          719.36         1538.31
Permanent Ineff=
       F       F
Bank Sta=584.8,599.8
XS Rating Curve= 0 ,0
Exp/Cntr=0.3,0.1

Type RM Length L Ch R = 1 ,9682.2  ,361.9,349.6,339.2
XS GIS Cut Line= 3
     2051092.962      243104.636      2050954.27      243657.457
     2050864.672      244194.549
#Sta/Elev= 30
       0 1729.24    26.2 1731.18    68.8 1720.84    81.9 1713.14    98.3 1695.05
   127.8 1679.11   140.8 1677.49     154 1670.12   170.3  1667.6   196.5 1654.16
   245.7 1636.44   258.8 1635.68   307.9 1623.17     380 1579.88   406.2 1566.65
   422.6 1555.02  452.391551.869  484.211549.502   501.2 1545.67   514.3  1534.9
   520.8 1532.31   533.9 1530.02   550.3 1533.26   560.1 1531.46   566.7 1529.73
  575.081531.466  625.811534.241  889.321534.885 1040.281535.788  1114.5 1549.74
#Mann= 8 ,-1 , 0
       0     .12       0  452.39    .016       0  484.21     .12       0
   560.1    .045       0  575.08     .12       0  625.81     .06       0
  889.32     .08       0 1040.28     .12       0
#XS Ineff= 2 , 0
                          732.05         1536.58
Permanent Ineff=
       F       F
Bank Sta=560.1,575.08
XS Rating Curve= 0 ,0
Exp/Cntr=0.3,0.1

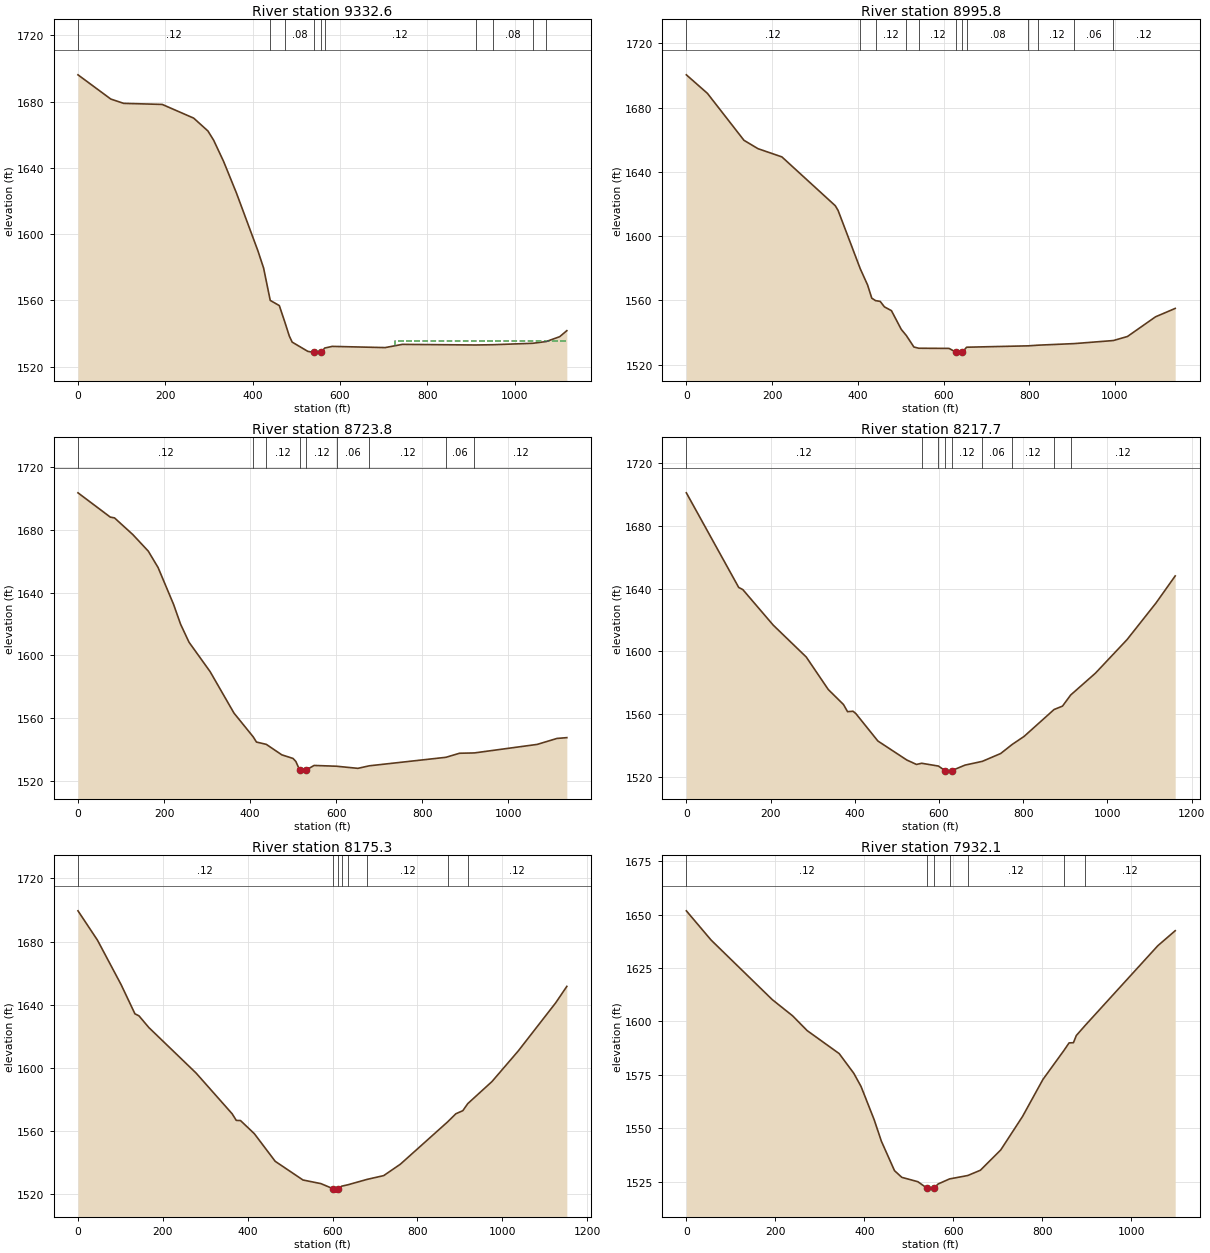
Type RM Length L Ch R = 1 ,9332.6  ,329.7,336.8,342.6
XS GIS Cut Line= 3
     2050454.129      243123.742     2050637.061      243648.869
     2050769.148      244196.843
#Sta/Elev= 30
       0 1696.19    75.2 1681.56   104.7 1678.96     193 1678.32     265 1670.06
   297.7 1662.29   310.8 1656.71   333.6  1643.9   363.1 1624.76   412.2 1589.92
   425.2 1579.55  440.411560.026   461.2 1556.89  473.921546.891   484.1  1538.5
   490.7 1534.83   526.6 1529.25  541.591528.597   549.5  1528.2  557.571528.742
  565.131531.261   582.3 1532.27   703.6 1531.54   742.9 1533.48  910.891533.118
  950.961533.275 1042.121534.143  1072.51535.186  1103.4 1538.12  1119.8 1541.75
#Mann= 10 ,-1 , 0
       0     .12       0  440.41    .016       0  473.92     .08       0
  541.59    .045       0  557.57     .08       0  565.13     .12       0
  910.89     .06       0  950.96     .08       0 1042.12     .06       0
  1072.5     .12       0
#XS Ineff= 2 , 0
                          726.13         1535.29
Permanent Ineff=
       F       F
Bank Sta=541.59,557.57
XS Rating Curve= 0 ,0
Exp/Cntr=0.3,0.1

Type RM Length L Ch R = 1 ,8995.8  ,270.4,272,269.8
XS GIS Cut Line= 2
     2050364.331      243146.787     2050332.134      244286.844
#Sta/Elev= 30
       0 1700.47    49.2 1688.92   134.4  1659.7   167.1 1654.48   222.9 1649.36
   347.4 1618.97     354 1616.02  405.861579.611   422.8 1569.62   432.6  1561.4
  441.311559.863   452.3 1559.37   462.1 1555.97   478.5  1553.6   501.4 1541.95
  513.241538.123   530.9 1530.96  542.361530.198   612.9  1530.1   629.2 1527.72
   635.8 1527.16  644.121527.707  653.791530.839  797.661531.696   821.41532.121
  905.181533.092  996.371535.003  1029.1 1537.52  1094.6 1549.77  1140.5    1555
#Mann= 12 ,-1 , 0
       0     .12       0  405.86    .016       0  441.31     .12       0
  513.24     .08       0  542.36     .12       0   629.2    .045       0
  644.12     .12       0  653.79     .08       0  797.66     .06       0
   821.4     .12       0  905.18     .06       0  996.37     .12       0
Bank Sta=629.2,644.12
XS Rating Curve= 0 ,0
Exp/Cntr=0.3,0.1

Type RM Length L Ch R = 1 ,8723.8  ,476.9,506,533.9
XS GIS Cut Line= 3
     2050116.879      243136.908      2050135.76      243691.753
     2050132.181      244272.405
#Sta/Elev= 30
       0 1703.49    75.1 1688.02    84.9 1687.51   127.4  1676.9   163.3 1666.36
   186.1 1655.91   222.1 1632.44   238.4 1619.79     258 1608.33     307  1589.6
   362.5 1563.17     4071548.105   414.7 1544.73  437.541543.273   473.5 1536.61
   499.6  1534.3   506.2 1532.38  514.971526.975   519.2 1526.22  530.671527.009
   548.6 1529.84  600.951529.333   650.3 1527.99  676.621529.601  854.881535.024
   886.5 1537.61   920.71537.807  1066.9 1543.24  1112.9 1547.04  1135.8 1547.55
#Mann= 9 ,-1 , 0
       0     .12       0     407    .016       0  437.54     .12       0
  514.97    .045       0  530.67     .12       0  600.95     .06       0
  676.62     .12       0  854.88     .06       0   920.7     .12       0
Bank Sta=514.97,530.67
XS Rating Curve= 0 ,0
Exp/Cntr=0.3,0.1

Type RM Length L Ch R = 1 ,8217.7  ,41.7,42.5,41.9
XS GIS Cut Line= 4
     2049934.049       243064.36     2049736.132      243629.465
     2049674.934      243654.204     2049388.476      244059.152
#Sta/Elev= 30
       0 1701.05   124.3 1640.72   134.2 1639.31   206.1 1616.72   284.7 1596.34
     337 1575.61     373 1566.08   382.8 1561.49   395.9 1561.75   402.4 1560.29
   454.8 1542.77   523.5 1530.65   546.4 1527.83   558.81528.574  598.731526.783
  613.851523.923   620.8 1523.56   630.21523.887   661.6 1527.39  702.79  1529.8
   746.4 1534.79  773.811540.602   801.8 1545.66  873.131562.846   893.2 1565.03
   912.61572.103   971.5 1586.06  1046.6 1607.48  1115.1 1630.74  1160.8 1648.05
#Mann= 9 ,-1 , 0
       0     .12       0   558.8    .016       0  598.73     .12       0
  613.85    .045       0   630.2     .12       0  702.79     .06       0
  773.81     .12       0  873.13     .06       0   912.6     .12       0
Bank Sta=613.85,630.2
XS Rating Curve= 0 ,0
Exp/Cntr=0.3,0.1

Type RM Length L Ch R = 1 ,8175.3  ,259.2,243.2,227.1
XS GIS Cut Line= 4
     2049906.705      243056.548     2049719.205      243594.308
     2049658.007      243619.048      2049359.83      244040.923
#Sta/Elev= 30
       0 1699.45    45.8 1680.94   101.5 1652.82   134.2 1634.29     144 1632.93
   166.9 1625.62   278.2 1596.83   363.3 1571.02   373.1 1566.82     383 1566.73
   415.7  1558.4   464.8 1540.94   530.2 1529.11   572.6 1526.81   600.2 1523.69
   604.1 1523.33   613.5 1523.63  621.461525.201  635.691526.049  681.351529.497
   720.5 1531.88   759.8 1539.11  871.451565.957   890.6 1571.03   906.9 1572.95
  918.63 1577.44   975.6 1591.38  1037.7 1610.79    1126 1641.28  1152.1 1651.63
#Mann= 8 ,-1 , 0
       0     .12       0   600.2    .045       0   613.5     .12       0
  621.46     .06       0  635.69    .016       0  681.35     .12       0
  871.45     .06       0  918.63     .12       0
Bank Sta=600.2,613.5
XS Rating Curve= 0 ,0
Exp/Cntr=0.3,0.1

Type RM Length L Ch R = 1 ,7932.1  ,340.6,350,359.4
XS GIS Cut Line= 3
     2049739.993      242995.308     2049482.355      243477.315
     2049221.287       243964.19
#Sta/Elev= 30
       0 1651.84    55.6 1638.15   193.1 1610.26   238.9 1602.65   271.6 1595.73
   343.6 1584.96   376.4 1575.75   392.7 1569.59   422.2 1554.01   438.5  1543.9
     468 1530.12   484.4    1527   520.4 1524.96  541.551521.864   546.5 1521.48
   556.4 1521.89   566.2 1523.91  591.671526.259  632.711527.858     661 1530.32
   706.7 1539.81   755.8 1555.52   801.5 1572.81  848.971586.475   860.4 1589.97
   870.2 1590.08   876.7 1593.43   896.61598.154  1059.8 1635.47    1099 1642.52
#Mann= 7 ,-1 , 0
       0     .12       0  541.55    .045       0   556.4     .12       0
  591.67    .016       0  632.71     .12       0  848.97     .06       0
   896.6     .12       0
Bank Sta=541.55,556.4
XS Rating Curve= 0 ,0
Exp/Cntr=0.3,0.1

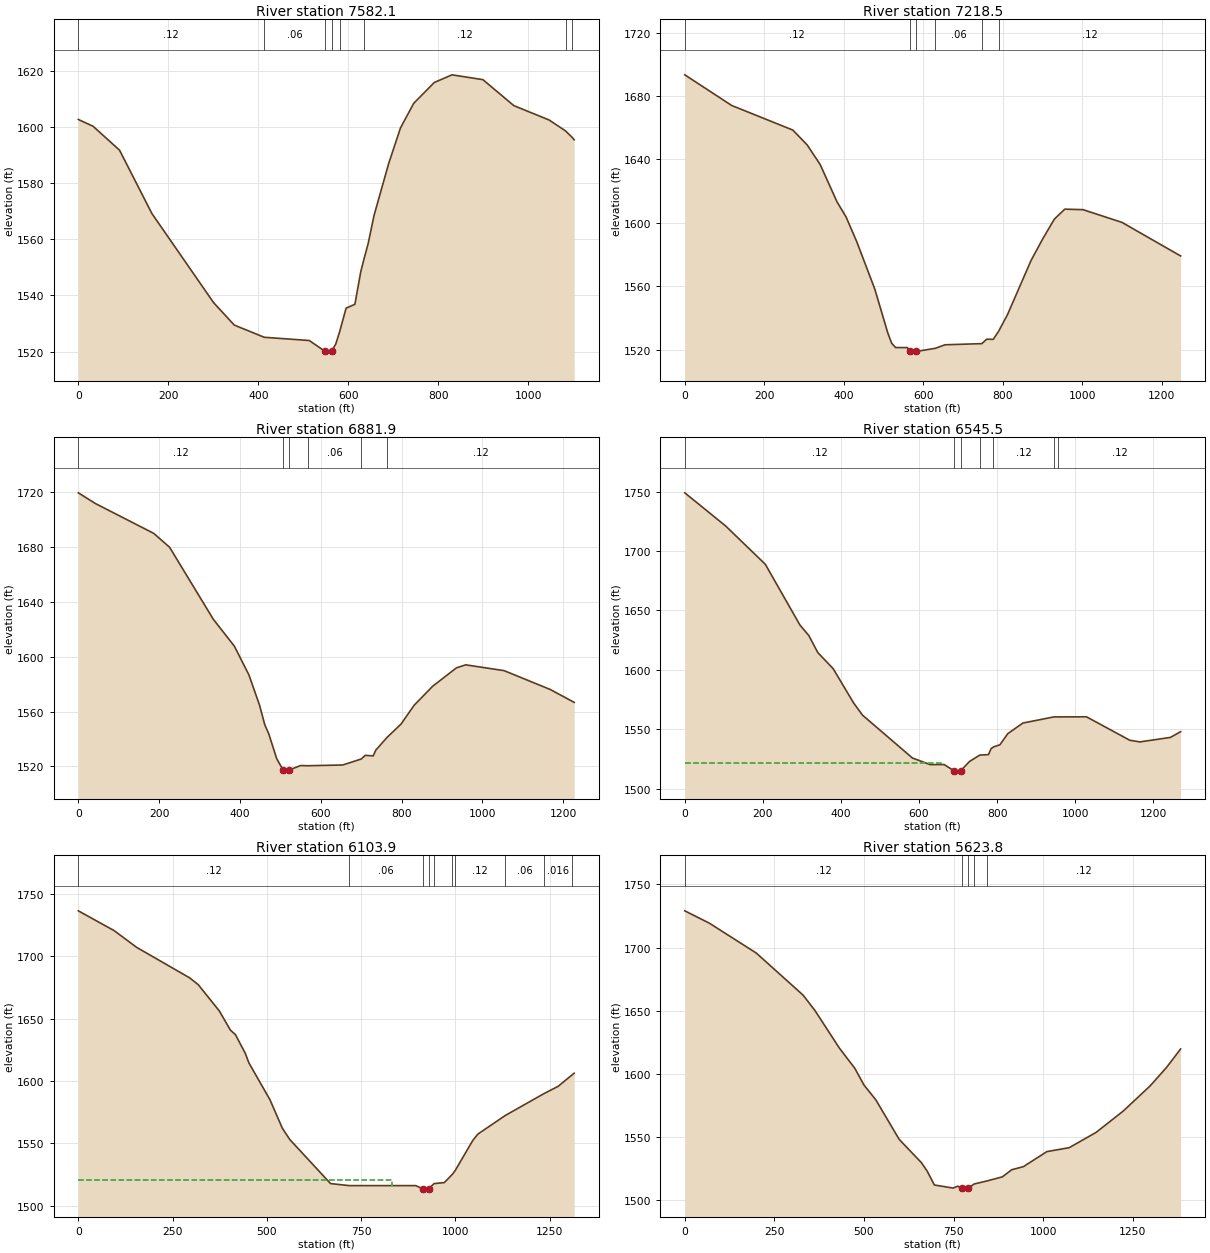
Type RM Length L Ch R = 1 ,7582.1  ,368.6,363.6,354
XS GIS Cut Line= 3
     2049634.466      242911.841     2049214.763      243276.397
     2048779.629      243606.642
#Sta/Elev= 30
       0 1602.63    32.7 1600.22    91.6 1591.71   163.5 1569.16   300.8 1537.42
   346.6 1529.46  413.261525.109   513.4 1523.96   548.4 1520.11   559.2 1519.47
   563.4 1520.28   572.3 1522.71  580.82 1527.04   595.2 1535.47   614.8 1536.85
   627.9  1548.5  635.06 1552.98   644.2  1558.4   657.3 1568.44     690 1587.02
   716.2 1599.64   745.6 1608.39   791.4 1615.81   830.7 1618.52   899.4  1616.8
   968.1 1607.56  1046.6 1602.44 1083.151598.552 1098.11 1596.21  1102.2  1595.4
#Mann= 8 ,-1 , 0
       0     .12       0  413.26     .06       0   548.4    .045       0
   563.4     .06       0  580.82    .016       0  635.06     .12       0
 1083.15     .06       0 1098.11     .12       0
Bank Sta=548.4,563.4
XS Rating Curve= 0 ,0
Exp/Cntr=0.3,0.1

Type RM Length L Ch R = 1 ,7218.5  ,339.1,336.6,326.5
XS GIS Cut Line= 2
     2049361.648      242483.025      2048677.62      243526.427
#Sta/Elev= 30
       0 1693.43   117.9 1674.09   271.8 1658.56   307.8 1649.24   340.6 1636.82
   383.1 1613.22     406 1603.62   432.2 1588.39   478.1 1558.18   510.8 1530.46
   520.7 1523.94   530.5 1521.27     560 1521.25   566.5  1518.8   573.1 1517.75
   582.9 1518.83  630.191520.779   654.9 1523.02   747.51523.748   759.7 1526.56
   776.1 1526.43  789.831531.619   812.1 1542.11     871 1576.11   900.5 1589.82
     930 1602.38   956.2 1608.64    1002 1608.32  1100.3 1600.25  1247.6 1579.09
#Mann= 6 ,-1 , 0
       0     .12       0   566.5    .045       0   582.9     .12       0
  630.19     .06       0   747.5    .016       0  789.83     .12       0
Bank Sta=566.5,582.9
XS Rating Curve= 0 ,0
Exp/Cntr=0.3,0.1

Type RM Length L Ch R = 1 ,6881.9  ,354.5,336.3,320.8
XS GIS Cut Line= 3
     2049034.182      242318.756     2048819.656      242789.217
      2048642.16      243476.566
#Sta/Elev= 30
       0 1719.06    42.5 1711.24   186.5 1689.59   225.8 1679.48   333.8  1627.2
   386.2 1607.49   422.2 1586.59   448.3 1564.74   461.4 1550.36   471.2 1543.79
   490.9 1525.73   507.2 1517.18   510.5 1516.63   520.3 1517.25   549.8  1520.7
  567.571520.547   654.5  1521.1  700.091525.452   710.1 1528.11   729.7  1527.7
   736.2 1531.92  764.091541.184   798.4  1550.8   831.1 1564.58   876.9 1578.37
   935.8 1591.78   958.7 1593.94  1053.6 1589.73  1168.1 1575.98    1227 1566.65
#Mann= 6 ,-1 , 0
       0     .12       0   507.2    .045       0   520.3     .12       0
  567.57     .06       0  700.09    .016       0  764.09     .12       0
Bank Sta=507.2,520.3
XS Rating Curve= 0 ,0
Exp/Cntr=0.3,0.1

Type RM Length L Ch R = 1 ,6545.5  ,417.4,441.6,465.1
XS GIS Cut Line= 4
     2048764.426      242274.691     2048488.384      242792.053
     2048566.509      242981.288     2048526.578      243458.719
#Sta/Elev= 30
       0 1748.99   104.8 1721.06   206.4 1688.84   294.8 1637.86   317.8 1628.87
   340.7 1614.62     380  1601.1   432.4 1572.25   455.4 1561.91   583.1 1525.92
   628.6 1520.34   664.4  1520.4   690.4    1515   703.4 1514.86   706.6 1515.12
   729.4 1522.99  755.551528.334   778.1 1528.76   784.6 1533.76  790.681535.175
   807.4 1537.07     827 1546.26   866.1 1555.31  946.011560.506  956.421560.469
    1029 1560.57  1139.9 1540.85  1165.9 1539.44  1244.2 1543.24  1270.2 1548.06
#Mann= 7 ,-1 , 0
       0     .12       0   690.4    .045       0   706.6     .12       0
  755.55    .016       0  790.68     .12       0  946.01     .06       0
  956.42     .12       0
#XS Ineff= 2 , 0
          660.15 1521.49
Permanent Ineff=
       F       F
Bank Sta=690.4,706.6
XS Rating Curve= 0 ,0
Exp/Cntr=0.3,0.1

Type RM Length L Ch R = 1 ,6103.9  ,469.9,480.1,489.8
XS GIS Cut Line= 2
     2048681.093      242206.983     2047879.009       243248.65
#Sta/Elev= 30
       0  1736.5    95.1  1720.6   154.1  1707.3   295.1 1682.76     318 1677.26
   373.8 1656.23   403.3 1640.81   416.4  1637.3   442.6  1622.3   452.4 1614.48
   508.2 1584.95     541 1562.12   560.6 1553.13   668.8 1517.75  718.291516.125
     895 1516.11  913.361513.559   924.5 1513.31  928.771513.607  943.371517.747
   970.4 1518.55  991.791525.185  999.39 1528.29  1045.8  1552.3    1059 1557.36
 1131.751572.312 1233.88 1589.78  1272.1 1595.73 1309.861605.095  1314.7 1606.28
#Mann= 10 ,-1 , 0
       0     .12       0  718.29     .06       0  913.36    .045       0
  928.77     .06       0  943.37    .016       0  991.79     .06       0
  999.39     .12       0 1131.75     .06       0 1233.88    .016       0
 1309.86     .12       0
#XS Ineff= 2 , 0
           832.3 1520.34
Permanent Ineff=
       F       F
Bank Sta=913.36,928.77
XS Rating Curve= 0 ,0
Exp/Cntr=0.3,0.1

Type RM Length L Ch R = 1 ,5623.8  ,483.7,493.8,508.3
XS GIS Cut Line= 3
     2048635.953      242146.219      2047825.19      242564.622
     2047358.176      242500.386
#Sta/Elev= 30
       0 1729.15    68.7 1719.36   199.5 1695.74   330.3 1662.41     363 1650.36
   431.6 1620.46   474.2 1604.68   500.3 1591.22     533 1579.67   598.4 1548.28
   660.6  1529.8   676.9 1522.98   696.5 1512.21   748.8 1509.77   761.9 1511.27
     775 1509.46   784.8 1508.93  790.031509.464  807.721513.012  842.951515.376
   886.2 1518.62   912.4 1524.27   945.1 1526.72  1010.6 1538.63  1072.8 1541.71
  1148.1 1553.86  1223.4 1570.66  1298.6 1590.59  1344.5 1605.22  1383.8 1619.86
#Mann= 5 ,-1 , 0
       0     .12       0     775    .045       0  790.03     .12       0
  807.72    .016       0  842.95     .12       0
Bank Sta=775,790.03
XS Rating Curve= 0 ,0
Exp/Cntr=0.3,0.1

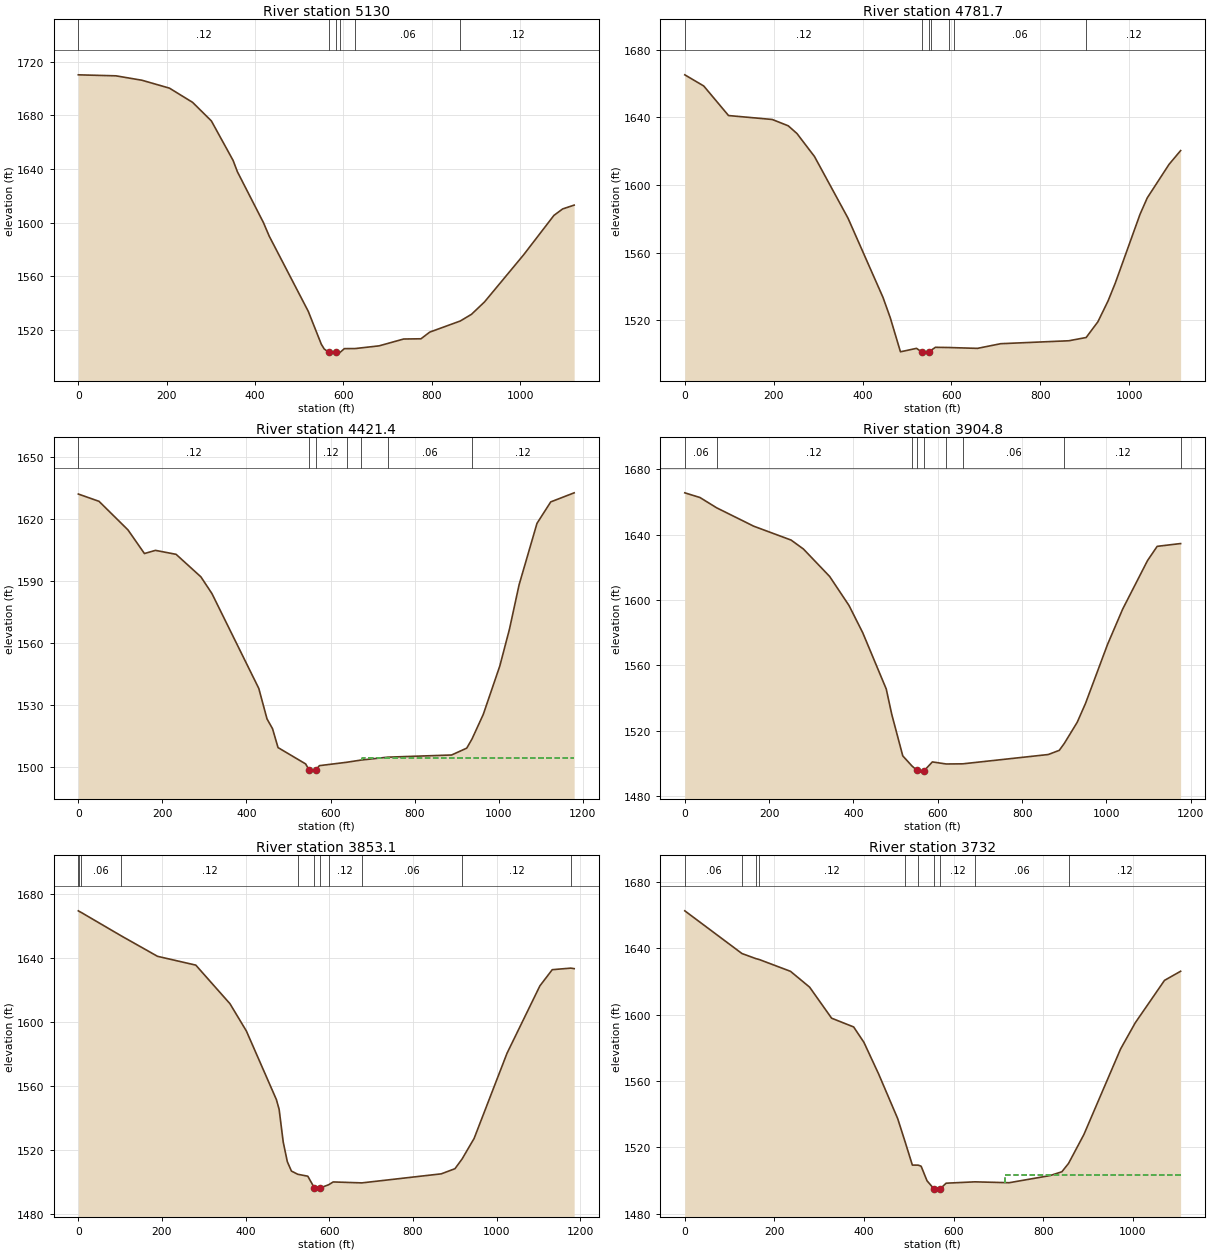
Type RM Length L Ch R = 1 ,5130    ,343,348.3,343.3
XS GIS Cut Line= 3
     2048621.597      242006.769     2048039.515      242030.274
     2047518.395      241890.461
#Sta/Elev= 30
       0 1710.23    85.1 1709.48     144 1706.19   206.2 1700.31   258.6 1689.72
   301.1 1675.88   350.2 1646.49     360    1638   418.9 1600.14     432 1590.04
   520.4 1533.99   549.8 1509.58   556.4 1505.99   566.2 1503.63   572.7 1502.88
   582.6 1503.76  591.781503.298   602.2 1506.24  626.241506.276   680.7  1508.3
   736.2 1513.39   775.5 1513.57   795.1 1518.51  864.511526.837   889.9 1531.84
   919.4 1541.09  1007.7 1576.11  1076.3 1605.48    1096  1610.3  1122.1 1613.16
#Mann= 6 ,-1 , 0
       0     .12       0   566.2    .045       0   582.6     .12       0
  591.78    .016       0  626.24     .06       0  864.51     .12       0
Bank Sta=566.2,582.6
XS Rating Curve= 0 ,0
Exp/Cntr=0.3,0.1

Type RM Length L Ch R = 1 ,4781.7  ,374.5,360.4,350.3
XS GIS Cut Line= 3
     2048661.418      241787.916     2048128.967      241692.283
     2047554.897       241714.36
#Sta/Elev= 30
       0 1665.21    42.6 1658.62    98.4 1641.14   196.7 1638.82   232.8 1635.07
   252.4  1630.5   291.8 1616.91   367.2 1580.49   445.9 1533.65   462.3  1521.6
   485.2 1501.49   521.3 1503.53   534.4 1501.18   544.2 1500.71   549.5  1501.2
  554.291502.427   563.8 1504.14  593.931504.037  605.211503.932   658.5 1503.52
   710.7 1506.28   864.1 1508.02  902.971509.942   929.4 1519.25   952.3 1531.59
   968.6 1542.18  1024.1 1582.73  1040.4 1592.46  1089.4 1612.27  1115.5 1620.43
#Mann= 7 ,-1 , 0
       0     .12       0   534.4    .045       0   549.5     .12       0
  554.29    .016       0  593.93     .12       0  605.21     .06       0
  902.97     .12       0
Bank Sta=534.4,549.5
XS Rating Curve= 0 ,0
Exp/Cntr=0.3,0.1

Type RM Length L Ch R = 1 ,4421.4  ,540.5,516.6,490.8
XS GIS Cut Line= 2
     2048594.287      241088.927     2047539.201      241616.502
#Sta/Elev= 30
       0 1632.22    49.2 1628.69     118 1614.85   157.3 1603.36   183.5  1604.9
   232.6 1602.98   291.6 1592.05   317.8 1583.97   429.3 1537.95   448.9 1523.14
     462 1518.42   475.1 1509.25   540.7 1501.32  549.621498.222     557 1497.82
  565.191498.328   573.4 1500.47  638.651502.121  672.011503.166  736.341504.595
     888 1505.64     924 1508.96  936.511513.374   963.4 1525.35  1002.7 1548.81
  1025.6  1566.6  1048.6 1588.21  1091.2 1618.01  1123.9 1628.41  1179.6 1632.81
#Mann= 7 ,-1 , 0
       0     .12       0  549.62    .045       0  565.19     .12       0
  638.65    .016       0  672.01     .12       0  736.34     .06       0
  936.51     .12       0
#XS Ineff= 2 , 0
                          675.18         1504.08
Permanent Ineff=
       F       F
Bank Sta=549.62,565.19
XS Rating Curve= 0 ,0
Exp/Cntr=0.3,0.1

Type RM Length L Ch R = 1 ,3904.8  ,44.6,51.7,48.5
XS GIS Cut Line= 4
     2048273.892      240763.579     2047785.611      240943.267
     2047777.799      241009.673     2047256.965      241284.413
#Sta/Elev= 30
       0 1665.64      36 1662.77    75.41656.489   163.6  1645.2     252 1636.74
   281.4 1631.24   343.6 1614.44   389.4 1596.72   422.1 1579.97   477.8 1545.57
   490.8 1530.13     517 1504.64  538.671498.483  551.051495.714   558.5  1495.3
     568 1495.66   587.2 1500.94  619.841499.673  659.361499.768     862 1505.46
   888.1    1508     9001512.219   930.7 1525.19   950.3 1536.66  1002.6 1572.81
  1038.6  1594.5  1097.5 1624.18  1120.4 1632.88 1175.881634.596    1176 1634.59
#Mann= 9 ,-1 , 0
       0     .06       0    75.4     .12       0  538.67    .016       0
  551.05    .045       0     568    .016       0  619.84     .12       0
  659.36     .06       0     900     .12       0 1175.88     .06       0
Bank Sta=551.05,568
XS Rating Curve= 0 ,0
Exp/Cntr=0.3,0.1

Type RM Length L Ch R = 1 ,3853.1  ,100.7,121.1,150
XS GIS Cut Line= 4
     2048267.382      240732.329     2047749.153      240922.433
      2047741.34       240988.84     2047240.038      241253.163
#Sta/Elev= 30
       0 1669.51    1.791669.212    6.581668.547  102.411653.895   189.4 1641.07
   280.9 1635.57   362.6 1611.44   401.8 1594.41   473.6 1551.52   480.1 1545.47
   489.9 1525.05   499.7 1512.73   509.5 1506.85  524.631504.836   548.7 1503.63
   564.7  1496.2   567.9 1495.55   577.5 1496.22  598.781498.315   609.3 1500.04
  678.041499.452   867.8  1505.1   900.6 1508.32  917.551514.367   946.4 1527.25
  1025.1  1580.5  1103.7 1622.62  1133.2 1632.72 1177.591633.702  1185.6 1633.36
#Mann= 11 ,-1 , 0
       0     .06       0    1.79     .12       0    6.58     .06       0
  102.41     .12       0  524.63    .016       0   564.7    .045       0
   577.5    .016       0  598.78     .12       0  678.04     .06       0
  917.55     .12       0 1177.59     .06       0
Bank Sta=564.7,577.5
XS Rating Curve= 0 ,0
Exp/Cntr=0.3,0.1

Type RM Length L Ch R = 1 ,3732    ,314.4,320.7,326.3
XS GIS Cut Line= 3
     2048215.833      240635.921     2047690.615      240840.518
     2047183.323      241034.656
#Sta/Elev= 30
       0 1662.66  127.621636.907  158.451633.857  166.261633.288     236 1626.17
   278.6 1616.64   327.7 1597.92   376.9 1592.64   399.8 1583.38   432.6 1564.32
   475.2 1537.39  492.041523.153     508 1509.33  521.04 1509.31   527.6 1508.64
   540.7 1499.87   556.2 1495.02   560.4 1494.84   570.2 1495.01   583.3 1498.42
   647.51499.235     724  1498.7   815.6 1503.02   841.8 1505.33  856.59 1510.34
   890.9 1527.78   972.7 1579.31  1005.4 1595.08  1070.8 1620.72  1106.8 1626.22
#Mann= 10 ,-1 , 0
       0     .06       0  127.62     .12       0  158.45     .06       0
  166.26     .12       0  492.04    .016       0  521.04     .12       0
   556.2    .045       0   570.2     .12       0   647.5     .06       0
  856.59     .12       0
#XS Ineff= 2 , 0
                          714.79         1503.48
Permanent Ineff=
       F       F
Bank Sta=556.2,570.2
XS Rating Curve= 0 ,0
Exp/Cntr=0.3,0.1

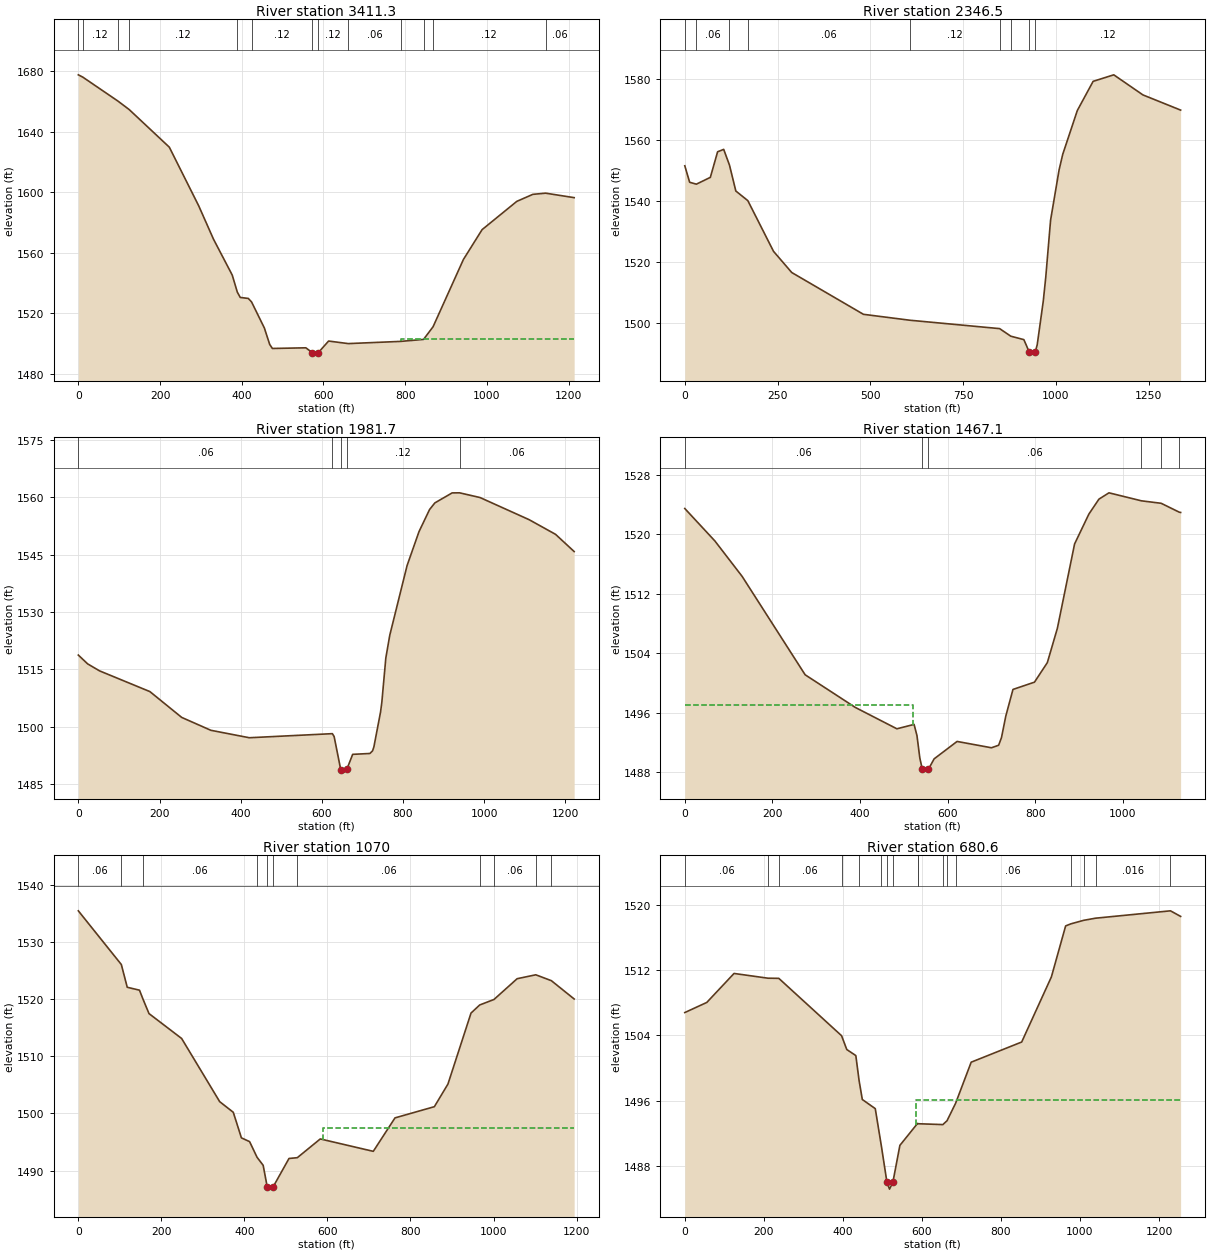
Type RM Length L Ch R = 1 ,3411.3  ,1068,1064.8,1054.2
XS GIS Cut Line= 3
     2048160.259      240477.816     2047505.745      240548.997
     2046991.856      240759.066
#Sta/Elev= 30
       0 1677.76    10.8 1676.26   96.561660.453   124.5 1654.76   222.7 1629.86
   294.8 1590.92   330.8 1568.95   376.7 1545.17  389.09 1533.91   396.3 1530.36
     416 1529.71  423.951527.416   455.3 1510.15   468.4 1499.22     475 1496.58
   556.8 1497.02   572.3 1493.89   576.5  1493.5   587.3 1493.82   612.5  1501.5
  660.741499.806  789.341501.275   844.91502.579  868.251510.983   942.5 1555.52
   988.2 1575.26  1073.1 1593.97  1112.3 1598.62 1143.611599.406  1213.5 1596.44
#Mann= 13 ,-1 , 0
       0     .06       0    10.8     .12       0   96.56     .06       0
   124.5     .12       0  389.09    .016       0  423.95     .12       0
   572.3    .045       0   587.3     .12       0  660.74     .06       0
  789.34     .12       0   844.9     .06       0  868.25     .12       0
 1143.61     .06       0
#XS Ineff= 2 , 0
                          789.07         1502.69
Permanent Ineff=
       F       F
Bank Sta=572.3,587.3
XS Rating Curve= 0 ,0
Exp/Cntr=0.3,0.1

Type RM Length L Ch R = 1 ,2346.5  ,369.6,364.8,365
XS GIS Cut Line= 2
     2047984.912      239894.483     2046760.954      240429.205
#Sta/Elev= 30
       0 1551.62    13.1 1546.22    31.21545.596    68.8 1547.83    88.4 1556.22
   104.8 1557.01  120.391551.841   137.5 1543.35   169.81540.194     239 1523.57
   288.1 1516.62   481.2 1502.91  606.171500.972  848.191498.216  878.211495.733
   913.4 1494.61  928.061490.499   939.6 1490.18  944.071490.534   949.4 1492.94
   965.7 1507.24   972.3 1514.95   985.4  1533.8  1008.3 1550.27  1018.1 1555.38
  1057.4 1569.75    1100 1579.32  1155.6 1581.46  1234.2 1574.87  1335.7 1569.89
#Mann= 9 ,-1 , 0
       0     .12       0    31.2     .06       0  120.39    .016       0
   169.8     .06       0  606.17     .12       0  848.19     .06       0
  878.21     .12       0  928.06    .045       0  944.07     .12       0
Bank Sta=928.06,944.07
XS Rating Curve= 0 ,0
Exp/Cntr=0.3,0.1

Type RM Length L Ch R = 1 ,1981.7  ,503,514.6,516.6
XS GIS Cut Line= 3
     2047623.656      239570.931     2047081.622      239941.041
     2046538.656      240098.165
#Sta/Elev= 30
       0  1518.7    22.9  1516.4    52.2 1514.57   176.3 1509.14   254.7 1502.38
   326.5 1499.01   421.2 1497.06  625.891498.127   630.2 1497.39   646.5 1488.71
   649.8 1488.32  661.371488.751   675.9 1492.71   718.4 1492.94     725 1493.64
   728.2 1494.67   744.6 1503.79   747.8 1506.38   757.6 1517.94   767.4 1523.93
   809.9 1542.11   839.3    1551   865.4  1556.8   878.5 1558.54     921 1561.15
  939.27 1561.17   989.6 1559.94  1110.5 1554.15  1175.8  1550.3  1221.6  1545.8
#Mann= 5 ,-1 , 0
       0     .06       0  625.89     .12       0   646.5    .045       0
  661.37     .12       0  939.27     .06       0
Bank Sta=646.5,661.37
XS Rating Curve= 0 ,0
Exp/Cntr=0.3,0.1

Type RM Length L Ch R = 1 ,1467.1  ,393,397.1,397.7
XS GIS Cut Line= 2
     2047597.759      239422.261     2046477.967      239588.927
#Sta/Elev= 30
       0 1523.44    68.7 1519.08   130.9 1514.32   274.8 1501.09   389.4  1496.7
   484.3 1493.83   523.5 1494.42   530.1 1492.92   536.6 1489.91  542.261488.404
   546.4 1488.14   556.2 1488.39   569.3 1489.79   621.7 1492.13   700.2 1491.28
   716.6 1491.62   723.1 1492.65   732.9 1495.53   749.3 1499.12   798.4  1500.1
   827.8 1502.73   850.7 1507.34     890 1518.68   922.7  1522.7   945.6  1524.7
   968.5 1525.55 1042.731524.474  1087.71524.143 1128.991522.948  1132.1 1522.91
#Mann= 6 ,-1 , 0
       0     .06       0  542.26    .045       0   556.2     .06       0
 1042.73     .08       0  1087.7     .06       0 1128.99     .12       0
#XS Ineff= 2 , 0
          520.25 1496.98
Permanent Ineff=
       F       F
Bank Sta=542.26,556.2
XS Rating Curve= 0 ,0
Exp/Cntr=0.3,0.1

Type RM Length L Ch R = 1 ,1070    ,412.9,389.3,365.1
XS GIS Cut Line= 3
     2047554.188       239125.97     2046835.438      239233.609
     2046467.382      239521.803
#Sta/Elev= 30
       0 1535.49  103.581526.083   117.8  1522.1   147.3 1521.59  155.821520.006
   170.2 1517.49   248.8 1513.13   340.5 1502.06   373.2  1500.2   392.8 1495.72
   412.5 1495.06  430.491492.316   445.2 1490.91     455 1487.12   464.9 1486.74
  469.071487.123   507.4 1492.11  527.451492.249   582.7 1495.53   710.4 1493.36
   762.7 1499.22   857.5 1501.18   890.2 1505.14   945.8 1517.58  966.651518.995
 1001.131519.963  1056.9  1523.6 1101.811524.284 1139.331523.253  1194.2 1520.05
#Mann= 11 ,-1 , 0
       0     .06       0  103.58    .016       0  155.82     .06       0
  430.49     .12       0     455    .045       0  469.07     .12       0
  527.45     .06       0  966.65     .08       0 1001.13     .06       0
 1101.81     .12       0 1139.33    .016       0
#XS Ineff= 2 , 0
                          588.68         1497.37
Permanent Ineff=
       F       F
Bank Sta=455,469.07
XS Rating Curve= 0 ,0
Exp/Cntr=0.3,0.1

Type RM Length L Ch R = 1 ,680.6   ,176.3,176.4,177.9
XS GIS Cut Line= 3
     2047075.021      238414.165     2046734.743      239181.526
     2046453.493      239487.081
#Sta/Elev= 30
       0 1506.81    55.7 1508.05   124.6  1511.6  210.511511.019  237.881511.001
  396.79 1503.97   409.9 1502.28   432.8 1501.54  441.111498.465   449.2 1496.16
     482 1495.04  497.671490.391   511.5 1486.03   518.1 1485.18   526.5 1486.01
   544.3 1490.54  588.961493.226  590.76 1493.19  653.041493.086  663.631493.561
  685.351495.705   724.7 1500.73   852.5  1503.2   927.7 1511.18   963.7 1517.42
  976.661517.672  1009.31518.108 1039.53 1518.37 1228.981519.272  1254.7 1518.59
#Mann= 17 ,-1 , 0
       0     .06       0  210.51    .016       0  237.88     .06       0
  396.79    .016       0  441.11     .06       0  497.67     .12       0
   511.5    .045       0   526.5     .12       0  588.96     .06       0
  590.76     .12       0  653.04     .06       0  663.63     .12       0
  685.35     .06       0  976.66    .016       0  1009.3     .08       0
 1039.53    .016       0 1228.98     .06       0
#XS Ineff= 2 , 0
                          585.14         1496.06
Permanent Ineff=
       F       F
Bank Sta=511.5,526.5
XS Rating Curve= 0 ,0
Exp/Cntr=0.3,0.1

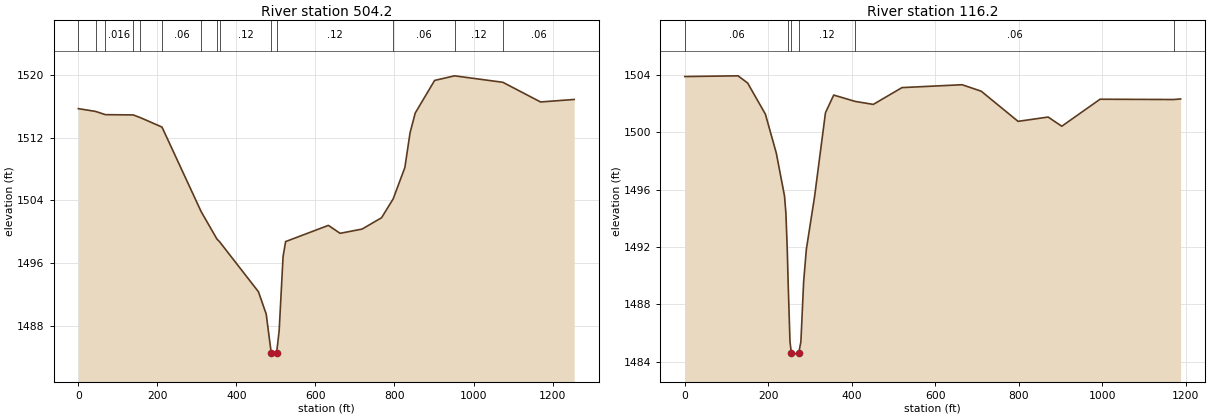
Type RM Length L Ch R = 1 ,504.2   ,385.7,388,389.1
XS GIS Cut Line= 3
     2046921.376       238336.04     2046581.098      239103.401
     2046299.848      239408.956
#Sta/Elev= 30
       0 1515.67   43.73 1515.32   68.341514.907  138.831514.873  156.881514.531
   211.71513.329  310.931502.569  350.751499.094  357.451498.748   455.8 1492.39
   475.4 1489.56  488.071484.635   491.8 1484.46   501.7 1484.62   508.2 1487.43
   518.1 1496.87   524.6 1498.77   632.8 1500.83   662.4 1499.82   718.1 1500.36
   767.3  1501.8  796.641504.192   826.3 1508.18   839.4 1512.59   852.5 1515.11
   901.6 1519.26  952.171519.844 1074.35 1519.02  1169.7 1516.52  1254.7 1516.84
#Mann= 14 ,-1 , 0
       0    .016       0   43.73     .08       0   68.34    .016       0
  138.83     .06       0  156.88    .016       0   211.7     .06       0
  310.93     .12       0  350.75     .06       0  357.45     .12       0
  488.07    .045       0   501.7     .12       0  796.64     .06       0
  952.17     .12       0 1074.35     .06       0
Bank Sta=488.07,501.7
XS Rating Curve= 0 ,0
Exp/Cntr=0.3,0.1

Type RM Length L Ch R = 1 ,116.2   ,102.8,116.2,129.7
XS GIS Cut Line= 2
     2046661.827       238219.72     2046078.493      239254.442
#Sta/Elev= 30
       0 1503.87   127.6 1503.92   150.5 1503.42   193.1 1501.25   219.2 1498.54
   238.9 1495.55   242.2 1494.35   245.4 1491.88  247.711489.395     252 1485.41
   255.2 1484.63   261.8 1484.54  272.981484.634   278.1  1485.4   284.7 1489.58
   291.2 1491.84   310.9 1495.51     337 1501.35   356.7 1502.58  408.091502.139
   451.6 1501.93   520.3  1503.1   664.3  1503.3   710.1 1502.85   798.4 1500.75
   870.4 1501.05   903.1 1500.41   994.8 1502.29 1171.61 1502.27  1187.8 1502.31
#Mann= 6 ,-1 , 0
       0     .06       0  247.71     .12       0   255.2    .045       0
  272.98     .12       0  408.09     .06       0 1171.61     .12       0
Bank Sta=255.2,272.98
XS Rating Curve= 0 ,0
Exp/Cntr=0.3,0.1

Chan Stop Cuts=-1
Use User Specified Reach Order=0
Composite Channel Slope=5